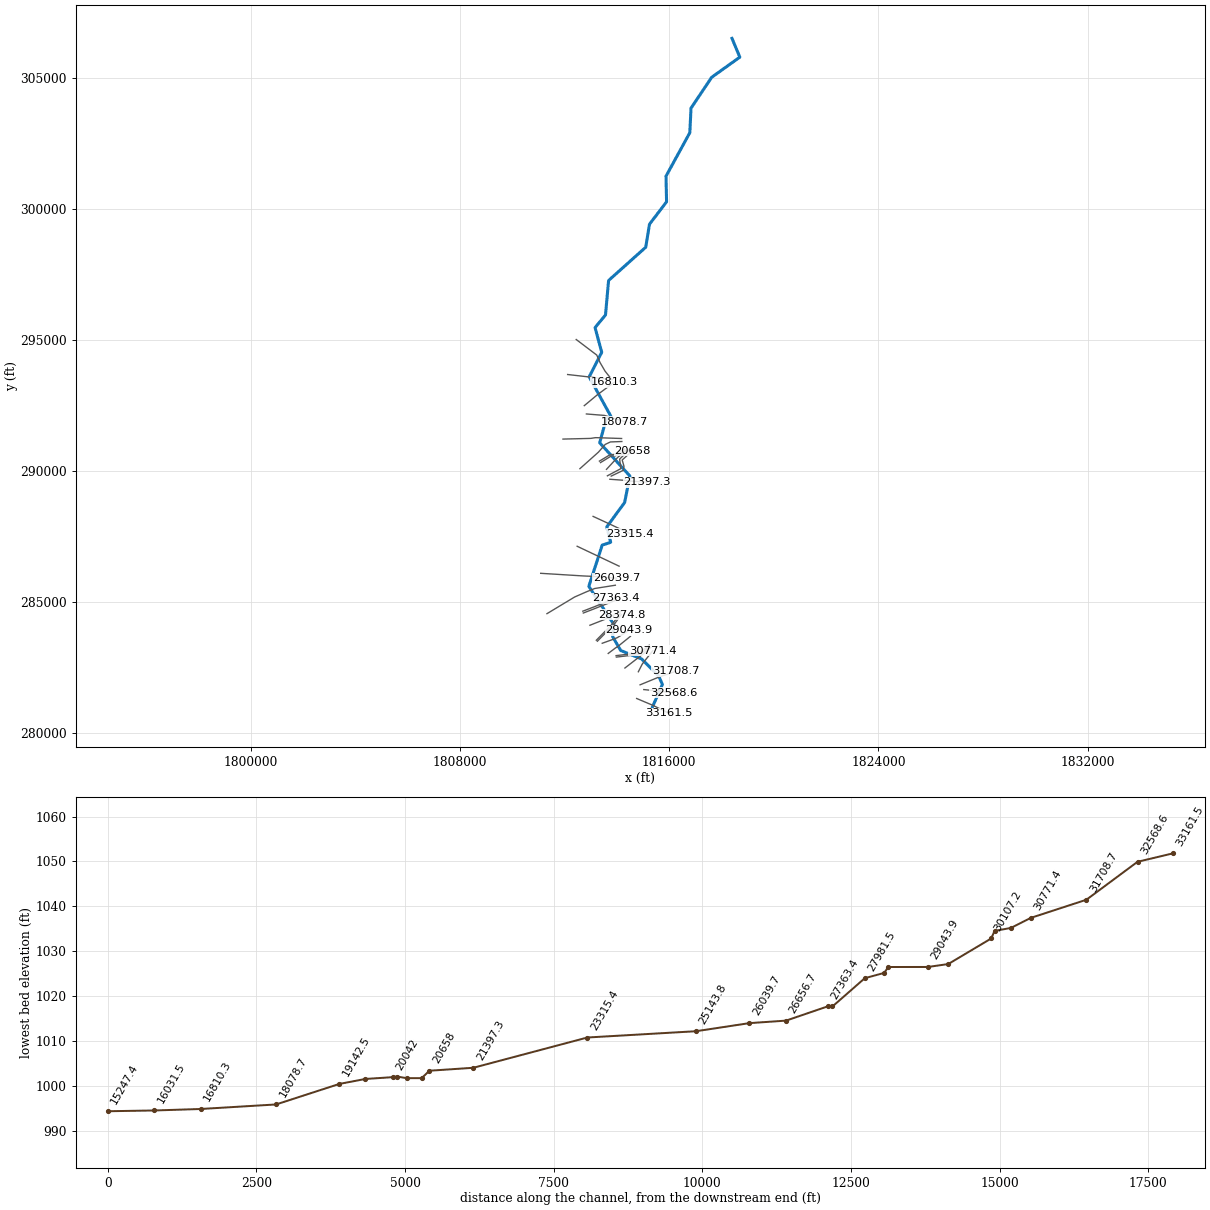
--- BerkeleyRn.prj (project) ---

Proj Title=BerkeleyRn
Current Plan=p01
Default Exp/Contr=0,0
English Units
Geom File=g01
Flow File=f01
Plan File=p01
BEGIN DESCRIPTION:
END DESCRIPTION:
DSS Export Rating Curves= 0
DSS Export Rating Curve Sorted= 0
DSS Export Volume Flow Curves= 0
DXF OffsetX= 0
DXF OffsetY= 0
DXF ScaleX= 0
DXF ScaleY= 0

--- BerkeleyRn.p01 (plan) ---

Plan Title=Floodplain
Program Version=4.00
Geom File=g01
Flow File=f01
K Sum by GR=0
Std Step Tol=0.01
Critical Tol=0.01
Num of Std Step Trials=20
Max Error Tol=0.3
Flow Tol Ratio=0.001
Split Flow NTrial=30
Split Flow Tol=0.02
Split Flow Ratio=0.02
Log Output Level=0
Friction Slope Method=1
Unsteady Friction Slope Method=2
Unsteady Bridges Friction Slope Method=1
Global Log Level=0
CheckData=False
Run HTab=0
Run UNet=0
Run PostProcess=0
UNET Theta=0
UNET Theta Warmup=0
UNET ZTol=0
UNET ZSATol=0
UNET MxIter=0
UNET MaxInSteps=0
UNET DtIC=0
UNET DtMin=0
UNET MaxCRTS=0
UNET WFStab=0
UNET SFStab=0
UNET WFX=0
UNET SFX=0
UNET DSS MLevel=0
UNET DZMax Abort=0
UNET Convert EG Bridges=0
UNET Use Existing IB Tables=0
UNET Froude Limit=0
UNET Froude Power=0
Write IC File=0
Echo Input=False
Echo Output=False
Write Detailed=0

--- BerkeleyRn.f01 (steady flow) ---

Flow Title=NFF Regression Equation
Program Version=4.10
Number of Profiles= 1
Profile Names=P100yr
River Rch & RM=BerkeleyRn,Main            ,33161.5
     518
River Rch & RM=BerkeleyRn,Main            ,30771.4
     602
River Rch & RM=BerkeleyRn,Main            ,29043.9
     642
River Rch & RM=BerkeleyRn,Main            ,26656.7
     708
River Rch & RM=BerkeleyRn,Main            ,26039.7
    1312
River Rch & RM=BerkeleyRn,Main            ,19582.9
    1445
River Rch & RM=BerkeleyRn,Main            ,19142.5
    2029
River Rch & RM=BerkeleyRn,Main            ,12208.1
    2194
River Rch & RM=BerkeleyRn,Main            ,4715.4
    2381
River Rch & RM=BerkeleyRn,Main            ,251.1
    2437
Boundary for River Rch & Prof#=BerkeleyRn,Main            , 1
Up Type= 0
Dn Type= 3
Dn Slope=0.00019
DSS Import GetInterval= 0
DSS Import GetPeak= 0
DSS Import FillOption= 0

--- BerkeleyRn.g01 (geometry) ---

Geom Title=USGS 10m DEM
Program Version=4.10

River Reach=BerkeleyRn      ,Main
Reach XY= 30
     1815364.401      280997.128     1815742.258      281852.938
     1815598.083      282174.077      1814944.67      282827.289
     1814148.187      283146.582     1813837.985      283681.662
     1813891.883       284132.64       1812929.6      285595.111
     1813441.804       287172.91     1813765.411      287279.556
     1813617.168       287869.59      1814299.78      288801.774
     1814499.349      289812.794     1813345.025      291081.684
     1813598.423      292001.727     1813803.036       292033.93
      1812943.61      293598.163     1813422.598      294536.595
     1813168.062      295478.268     1813567.007      295961.864
     1813685.184      297278.985     1815105.795      298549.235
     1815247.583      299425.693     1815901.353      300283.926
     1815879.922      301261.503     1816790.084      302922.917
     1816836.071      303860.364     1817625.603      305038.955
      1818701.42      305808.278     1818401.592      306526.693

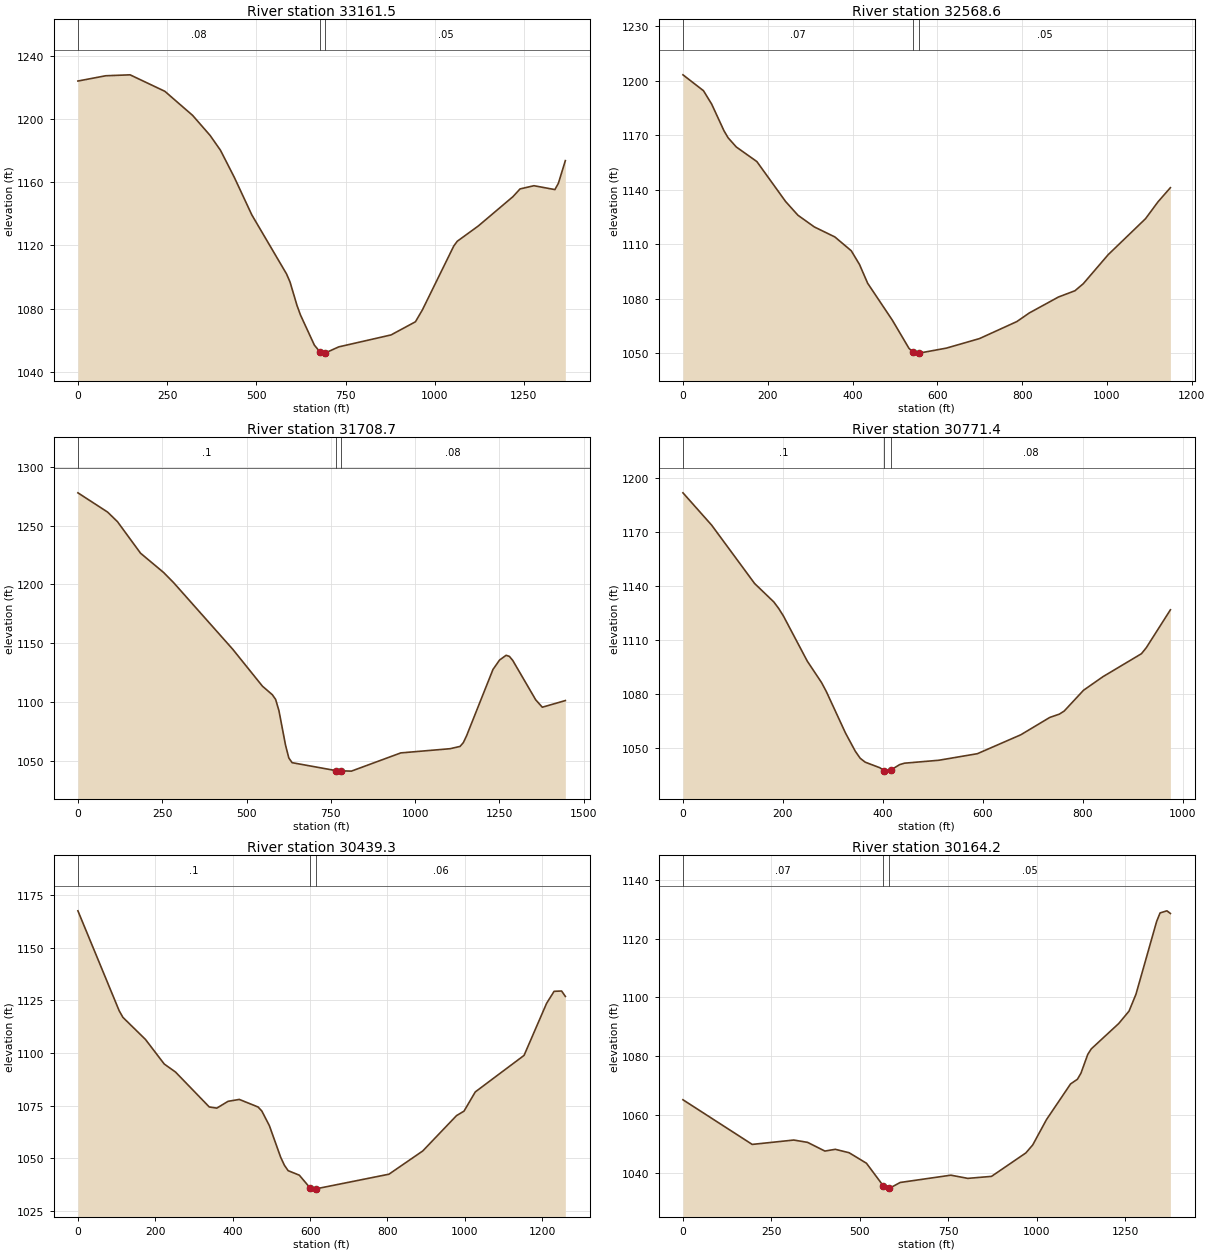
Type RM Length L Ch R = 1 ,33161.5 ,586.7,592.9,600.4
XS GIS Cut Line= 3
     1814757.815      281315.014     1815386.173      281049.261
     1815999.287      280746.155
#Sta/Elev= 30
       0 1224.02      78 1227.36   146.2 1227.95   243.7 1217.52   321.6 1202.26
   370.4 1189.62   399.6  1180.2   438.6 1162.95   487.3 1139.36   584.8  1101.9
   594.5 1096.84     614 1082.02   623.8 1075.94   662.8 1056.85   678.5 1052.56
     692  1051.8   693.5 1051.92   731.1 1055.76   877.7 1063.32     946 1071.64
   965.6  1079.2  1053.5 1119.61  1063.3 1122.62  1121.9 1132.22  1219.6 1150.89
  1239.2 1155.73  1278.2 1157.76  1336.9 1155.31  1346.6 1159.25  1366.2 1173.64
#Mann= 3 , 0 , 0
       0     .08       0   678.5    .045       0   693.5     .05       0
Bank Sta=678.5,693.5
XS Rating Curve= 0 ,0
Exp/Cntr=0.3,0.1

Type RM Length L Ch R = 1 ,32568.6 ,844.9,859.9,871.7
XS GIS Cut Line= 4
     1815029.829      281655.226       1815511.6      281607.483
     1815696.062      281583.612     1816173.493      281538.039
#Sta/Elev= 30
       0 1203.32    48.4 1194.57    67.8 1187.15    96.8 1172.48   106.5 1168.62
   125.9 1163.53   174.3 1155.52   242.1  1133.5   271.1 1125.95   309.8 1119.49
   358.3 1113.97     397 1106.34   416.4  1098.8   435.7 1088.42   493.9 1068.09
   533.1 1052.57   542.9 1050.43   552.7 1049.93   557.2 1049.94   621.2 1052.68
   699.5 1057.95   787.6 1067.33     817 1072.08   885.5 1080.84   924.6 1084.31
   944.2 1088.18  1002.9 1104.18    1091 1124.01  1120.4  1133.3  1149.7 1141.12
#Mann= 3 , 0 , 0
       0     .07       0   542.9    .045       0   557.2     .05       0
Bank Sta=542.9,557.2
XS Rating Curve= 0 ,0
Exp/Cntr=0.3,0.1

Type RM Length L Ch R = 1 ,31708.7 ,912.3,937.3,950
XS GIS Cut Line= 3
     1814888.985      281836.642     1815602.924      282130.412
     1816240.018      282348.542
#Sta/Elev= 30
       0 1277.78      88 1261.44   117.3 1253.29   185.7 1226.53   254.1 1210.14
   283.4 1201.64   459.3  1144.9   547.2  1113.6   576.6 1106.34   586.3 1102.35
   596.1 1092.83   615.7 1063.48   625.4 1052.67   635.2 1048.65   764.5 1041.95
   779.5 1041.75     811 1041.48   957.4 1056.95  1103.8 1060.52  1133.1 1062.46
  1142.9 1065.69  1152.6 1071.55  1230.7 1127.75  1250.2 1135.77  1269.8 1139.85
  1279.5 1138.88  1289.3 1135.53  1357.6 1101.99  1377.1 1095.75  1445.4 1101.39
#Mann= 3 , 0 , 0
       0      .1       0   764.5    .045       0   779.5     .08       0
Bank Sta=764.5,779.5
XS Rating Curve= 0 ,0
Exp/Cntr=0.3,0.1

Type RM Length L Ch R = 1 ,30771.4 ,338.7,332.1,297.1
XS GIS Cut Line= 4
     1814822.679      282335.757     1814970.248      282625.687
     1815077.887      282766.312     1815373.026      283136.104
#Sta/Elev= 30
       0 1191.66    57.4 1173.76   143.5 1141.38   181.8 1131.21   191.4 1127.66
   200.9 1123.51   248.8 1098.41   277.5 1086.46     287 1081.51   325.3 1058.56
     345 1048.43   354.8 1044.54   364.7  1042.4   394.2 1039.29   402.2 1037.77
     404 1037.43   417.2 1038.24   433.6 1041.03   443.4 1041.83   512.1 1043.45
   589.3 1047.09   676.2 1057.57   734.2 1067.19   753.5 1069.03   763.1 1070.74
   801.7 1082.24   840.4 1089.73   917.6 1102.49   927.3 1105.81   975.6 1126.82
#Mann= 3 , 0 , 0
       0      .1       0   402.2    .045       0   417.2     .08       0
Bank Sta=402.2,417.2
XS Rating Curve= 0 ,0
Exp/Cntr=0.3,0.1

Type RM Length L Ch R = 1 ,30439.3 ,286.9,275.1,286.5
XS GIS Cut Line= 4
     1814309.224      282478.552     1814746.435      282817.093
     1814878.234      282913.882     1815296.419      283260.566
#Sta/Elev= 30
       0 1167.65   106.7 1120.07   116.4 1116.93   174.6 1106.44   223.1 1094.74
   252.2 1090.93   339.5  1074.3   358.9 1073.75     388 1076.99   417.1 1077.89
   465.6 1074.29   475.4 1072.35   494.8 1065.41   523.9 1050.42   533.6 1046.59
   543.3 1043.98   572.2 1041.84   600.2 1035.74   610.7  1035.2   615.2 1035.34
   803.8  1042.3   891.1 1053.35   978.4 1070.18   997.8 1072.32  1026.9 1081.46
    1153 1098.85  1211.2 1123.62  1230.6 1129.34    1250 1129.49  1259.7 1126.92
#Mann= 3 , 0 , 0
       0      .1       0   600.2    .045       0   615.2     .06       0
Bank Sta=600.2,615.2
XS Rating Curve= 0 ,0
Exp/Cntr=0.3,0.1

Type RM Length L Ch R = 1 ,30164.2 ,57,57,57.9
XS GIS Cut Line= 5
     1813982.183      282895.983     1814516.905      282958.483
     1814621.072      282963.691     1814858.919      282989.733
      1815251.28      283293.552
#Sta/Elev= 30
       0 1065.04   195.8  1049.8   313.2 1051.29   352.4  1050.5   401.3 1047.53
   430.7 1048.13   469.8 1046.96   518.8 1043.38   566.8  1035.6   576.3 1034.54
   583.1 1034.78   614.2 1036.81   757.5  1039.3   805.4 1038.21   872.4 1038.89
   969.5 1046.89     989 1049.63  1027.9 1058.28    1096 1070.45  1115.4 1072.04
  1125.2 1074.08  1144.6 1080.53  1154.4 1082.39  1232.2 1091.07  1261.4 1095.32
  1280.9 1101.07  1339.2 1125.86    1349  1128.8  1368.4 1129.52  1378.2 1128.62
#Mann= 3 , 0 , 0
       0     .07       0   566.8    .045       0   583.1     .05       0
Bank Sta=566.8,583.1
XS Rating Curve= 0 ,0
Exp/Cntr=0.3,0.1

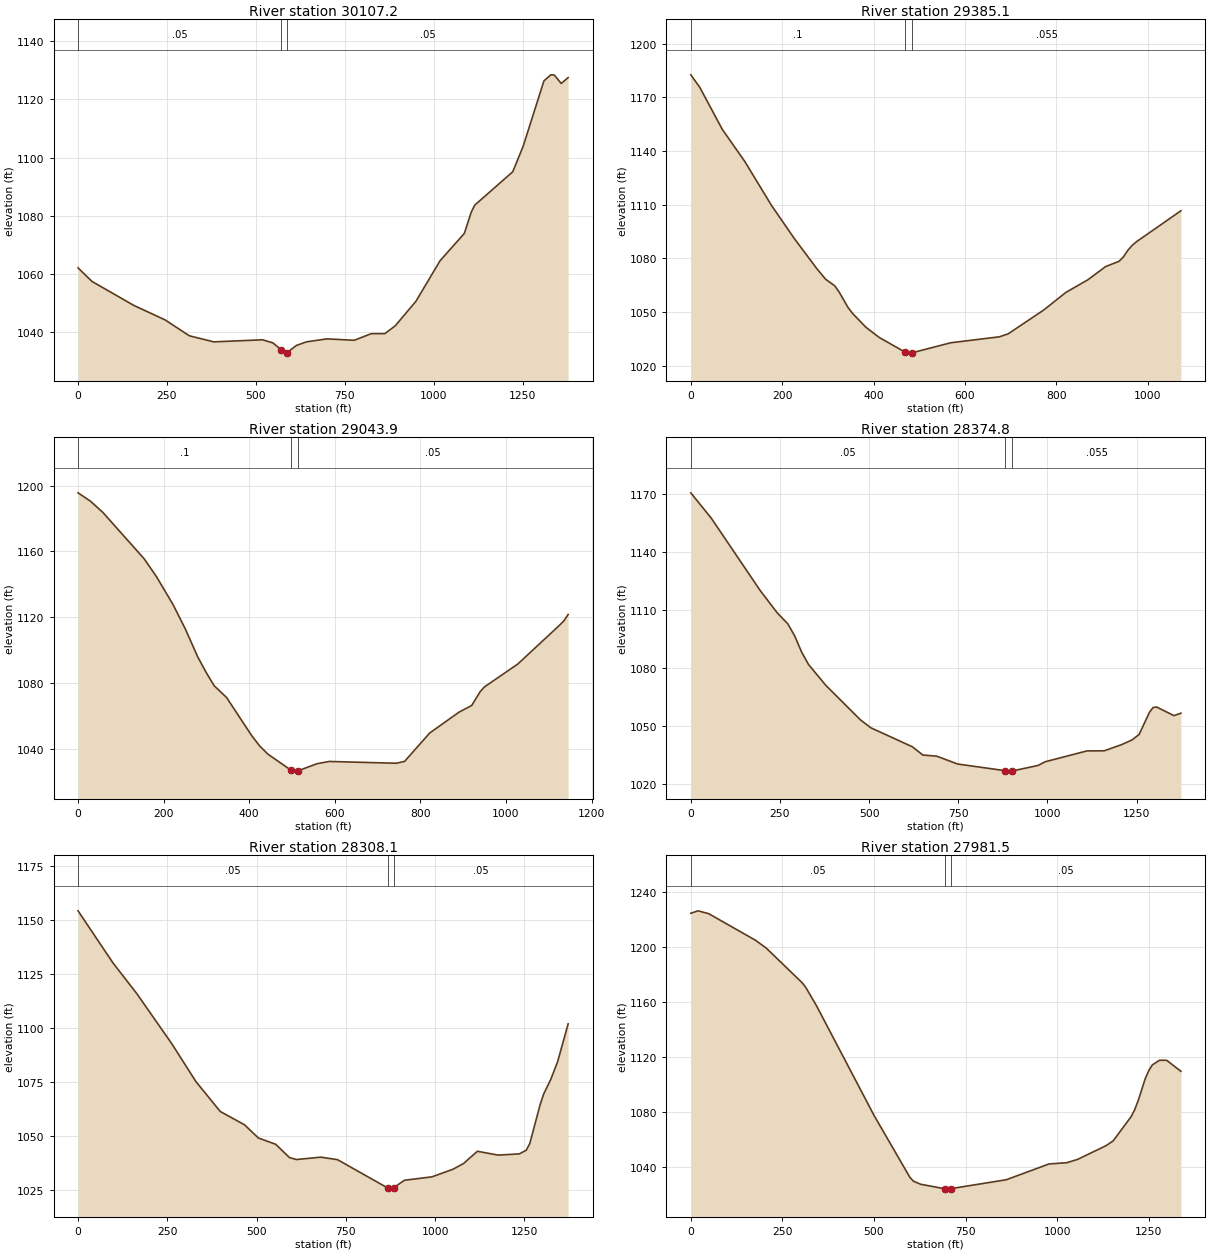
Type RM Length L Ch R = 1 ,30107.2 ,706.9,722,720.9
XS GIS Cut Line= 5
      1813970.03      282951.538     1814504.752      283014.038
     1814608.919      283019.247     1814846.766      283045.288
     1815239.127      283349.108
#Sta/Elev= 30
       0 1062.14    39.2 1057.48   156.6 1049.26   244.7 1044.27   313.2 1038.79
   381.8 1036.72   518.8 1037.43   547.8 1036.38   571.6 1034.01   585.8 1032.85
   586.6  1032.9   614.2  1035.5   642.7 1036.73   700.1 1037.75   776.6 1037.26
   824.5 1039.53   862.8 1039.55   891.7  1042.2     950 1050.63  1018.2 1064.62
  1086.3 1073.98  1105.7 1081.27  1115.4 1083.67  1222.5 1095.16  1251.7 1103.91
  1310.1 1126.37  1329.5 1128.45  1339.2 1128.39  1358.7 1125.49  1378.2  1127.5
#Mann= 3 , 0 , 0
       0     .05       0   571.6    .045       0   586.6     .05       0
Bank Sta=571.6,586.6
XS Rating Curve= 0 ,0
Exp/Cntr=0.3,0.1

Type RM Length L Ch R = 1 ,29385.1 ,345.4,341.2,336.7
XS GIS Cut Line= 4
     1813670.985      283034.872     1813929.666      283231.052
     1814075.499      283330.011     1814519.943      283689.386
#Sta/Elev= 30
       0 1182.53    19.7 1175.52    68.9 1152.09   118.1 1134.18   177.1 1109.43
   226.3 1091.23   275.5 1074.42   295.1  1068.4   314.8 1064.78   324.7 1061.24
   344.2 1052.59     354 1049.33   383.4 1041.55   412.8 1035.83   469.6 1027.63
   481.3 1027.16   484.6 1027.38   568.7 1032.94   675.3 1036.27   694.6 1037.94
   772.2 1051.21   820.6 1061.02     869 1068.13   907.8 1075.49   936.8 1078.39
   946.5 1080.79   956.2 1084.52   965.9 1087.31   975.6 1089.42  1072.5 1106.63
#Mann= 3 , 0 , 0
       0      .1       0   469.6    .045       0   484.6    .055       0
Bank Sta=469.6,484.6
XS Rating Curve= 0 ,0
Exp/Cntr=0.3,0.1

Type RM Length L Ch R = 1 ,29043.9 ,657.6,669.1,674.4
XS GIS Cut Line= 4
     1813441.776      283423.459     1813849.762      283571.029
     1814019.033      283638.303     1814468.252      283918.251
#Sta/Elev= 30
       0 1195.63    28.9 1190.57    57.8 1183.78   154.3 1155.62   183.2 1144.73
   221.8 1127.84   250.7 1112.91   279.6 1095.99   298.9 1086.71   318.2 1078.37
   347.1 1071.25   404.9 1048.44   424.2 1041.88   443.4 1036.89   498.2 1026.98
   510.6 1026.51   513.2 1026.64   558.5 1031.01   587.2 1032.39   743.4  1031.3
     763 1032.41   821.8 1049.68   890.5 1062.39   919.9  1066.4   939.5 1074.72
   949.3 1077.61  1027.7 1091.61  1125.7 1115.31  1135.5 1117.88  1145.3 1121.72
#Mann= 3 , 0 , 0
       0      .1       0   498.2    .045       0   513.2     .05       0
Bank Sta=498.2,513.2
XS Rating Curve= 0 ,0
Exp/Cntr=0.3,0.1

Type RM Length L Ch R = 1 ,28374.8 ,67,66.7,66.5
XS GIS Cut Line= 5
     1813257.313      283502.667     1813741.351      283993.801
     1813844.224      284083.791     1813931.464      284190.562
     1814175.489      284520.219
#Sta/Elev= 30
       0 1170.77    58.3  1157.4   194.2 1120.23   242.8 1108.44   271.9  1102.9
   291.4 1096.58   310.8  1088.2   330.2 1081.75   378.8 1070.93   475.9 1053.03
     505 1048.95   621.6 1039.09   650.7 1034.84   689.6 1034.26   748.2 1030.19
   881.4 1026.73   890.6  1026.5   901.7  1026.6   973.9 1029.45   993.4 1031.34
  1110.6 1036.97  1159.4 1037.04  1208.3 1040.25  1237.6  1042.7  1257.1 1045.51
  1286.4  1057.1  1296.2 1059.44  1305.9 1059.76  1354.8 1055.28  1374.3 1056.53
#Mann= 3 , 0 , 0
       0     .05       0   881.4    .045       0   901.7    .055       0
Bank Sta=881.4,901.7
XS Rating Curve= 0 ,0
Exp/Cntr=0.3,0.1

Type RM Length L Ch R = 1 ,28308.1 ,335.3,326.6,313.1
XS GIS Cut Line= 5
     1813216.081      283539.559     1813700.118      284030.694
      1813797.84      284129.804      1813882.41      284232.777
     1814134.256      284557.111
#Sta/Elev= 30
       0 1154.12    97.1 1130.17   165.1 1115.64   262.2 1092.65   330.2    1075
   398.2 1061.17   466.2    1055     505 1048.88   553.6 1045.96   592.4 1039.77
   611.9  1038.9   679.9    1040   726.7 1038.84   866.8 1025.77   876.3 1025.19
   884.5 1025.92   914.4 1029.31   991.3 1030.88    1050  1034.4  1079.3 1037.02
  1118.4 1042.72  1177.1 1040.95  1235.8 1041.51  1255.3 1043.22  1265.1 1046.28
  1294.4 1064.47  1304.2  1069.3  1323.8 1075.98  1343.3 1084.31  1372.6 1101.78
#Mann= 3 , 0 , 0
       0     .05       0   866.8    .045       0   884.5     .05       0
Bank Sta=866.8,884.5
XS Rating Curve= 0 ,0
Exp/Cntr=0.3,0.1

Type RM Length L Ch R = 1 ,27981.5 ,545.3,544.3,542.2
XS GIS Cut Line= 3
      1812971.94      284111.608     1813537.435      284335.045
     1814193.685       284654.49
#Sta/Elev= 30
       0 1224.73    19.6 1226.51      49 1224.42   176.5 1205.11     206 1199.39
     304 1174.18   313.8 1170.83   343.2 1157.41   500.2 1077.66   598.2 1032.54
     608 1029.76   627.5 1027.55  693.43 1024.27   705.4 1024.01  710.97 1024.41
   861.1 1030.83   977.8 1042.32  1026.5 1043.24  1055.7 1045.63  1133.5 1055.62
    1153 1059.14  1201.7 1076.63  1211.4 1081.53  1221.1 1088.28  1240.6 1104.45
  1250.3  1110.3    1260 1114.43  1279.5 1117.77    1299 1117.76  1337.9 1109.76
#Mann= 3 , 0 , 0
       0     .05       0  693.43    .045       0  710.97     .05       0
Bank Sta=693.43,710.97
XS Rating Curve= 0 ,0
Exp/Cntr=0.3,0.1

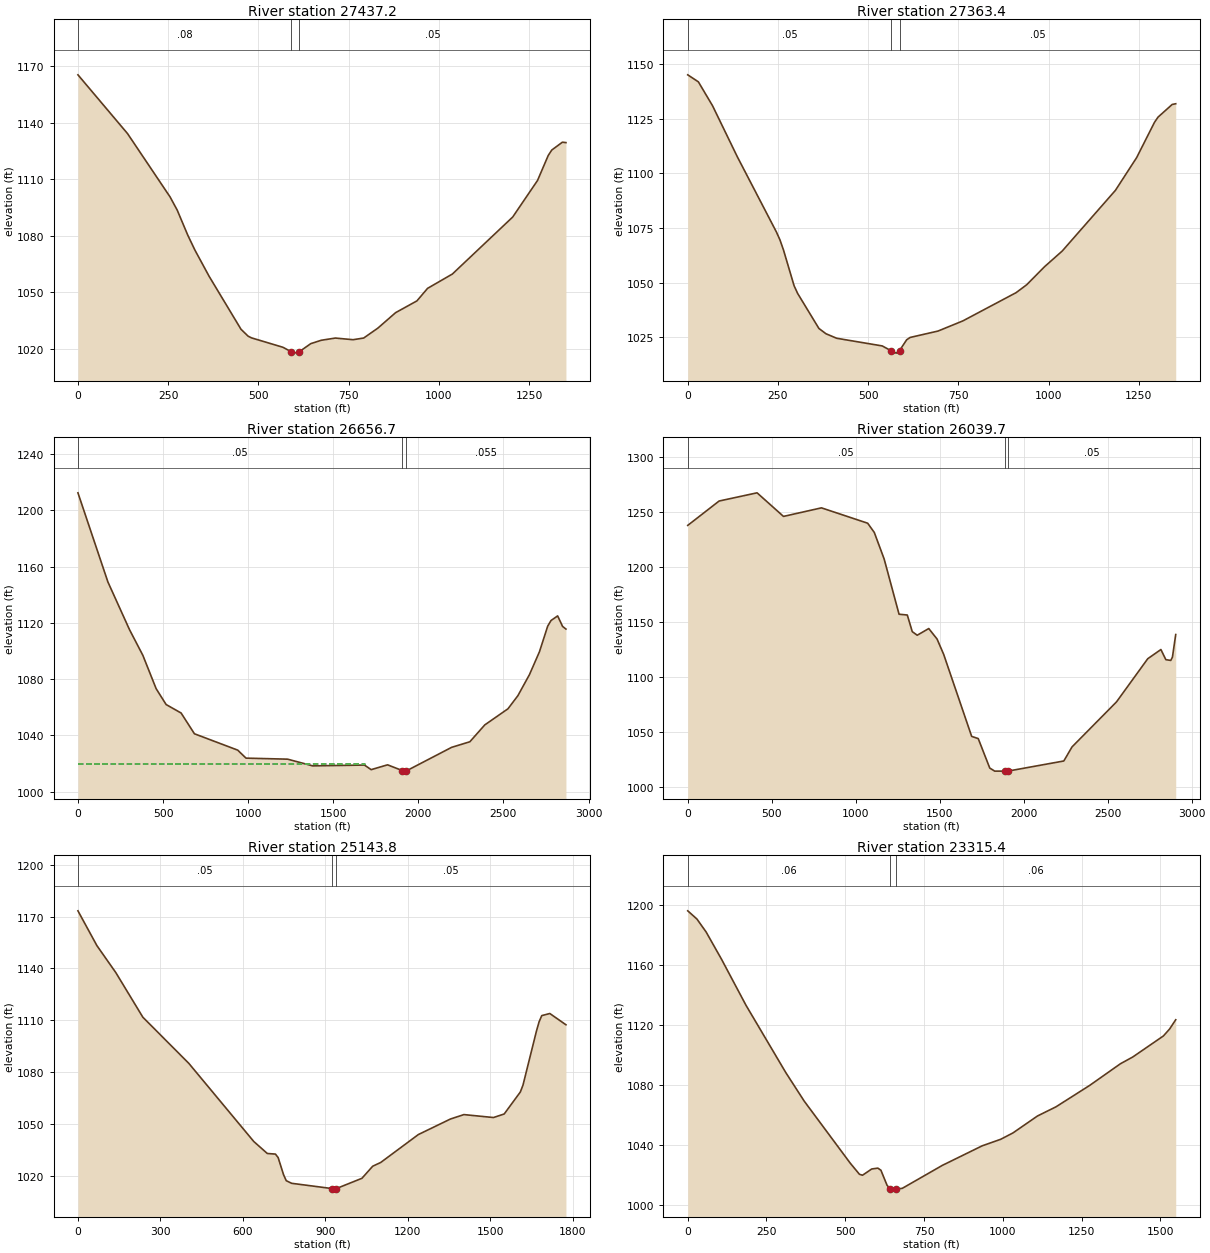
Type RM Length L Ch R = 1 ,27437.2 ,74.3,73.8,73.8
XS GIS Cut Line= 4
     1812718.468      284578.622     1813158.572      284747.893
     1813364.301      284831.226     1813978.884      285068.205
#Sta/Elev= 30
       0 1165.57   137.5 1134.33   255.4 1100.67   275.1 1093.68   304.5 1080.33
   324.2 1072.44   363.5 1058.53   451.9 1030.37   471.5 1026.73   481.2  1025.8
     568 1020.82  590.98 1018.46   606.6 1017.71     612 1018.28   645.2 1022.75
   674.2 1024.54   713.2 1025.72   762.3 1024.84   791.8 1025.73   831.1    1031
   880.3 1039.22   939.3 1045.46   968.8 1052.12  1037.6 1059.74  1204.7 1090.02
  1273.5 1109.45    1303 1122.66  1312.9  1125.6  1342.4 1129.78  1352.2 1129.55
#Mann= 3 , 0 , 0
       0     .08       0  590.98    .045       0     612     .05       0
Bank Sta=590.98,612
XS Rating Curve= 0 ,0
Exp/Cntr=0.3,0.1

Type RM Length L Ch R = 1 ,27363.4 ,701.6,706.6,697.3
XS GIS Cut Line= 4
     1812700.239      284648.934     1813140.343      284818.205
     1813346.072      284901.538     1813960.655      285138.518
#Sta/Elev= 30
       0 1145.02    29.5 1141.81    68.8 1130.87   137.5 1107.52   245.6  1073.2
   255.4 1069.61   265.2    1065   294.7 1048.58   304.5 1045.07   363.5 1029.04
   383.1 1026.62   412.6 1024.56   539.1 1021.05  563.31 1018.86   577.7 1017.76
   587.1 1018.96   606.6 1023.85   616.3 1024.93   693.5 1027.85   762.3 1032.49
   909.8  1045.4   939.3 1049.03   988.4 1057.23  1037.6 1064.43  1185.1 1092.19
    1244 1107.19  1293.2 1123.25    1303 1125.65  1342.4 1131.47  1352.2 1131.79
#Mann= 3 , 0 , 0
       0     .05       0  563.31    .045       0   587.1     .05       0
Bank Sta=563.31,587.1
XS Rating Curve= 0 ,0
Exp/Cntr=0.3,0.1

Type RM Length L Ch R = 1 ,26656.7 ,624.8,617,576.7
XS GIS Cut Line= 5
     1811329.101      284553.795     1812384.657      285189.212
      1812842.99      285390.601      1813155.49      285515.601
     1813943.685      285640.601
#Sta/Elev= 30
       0 1212.54     176 1149.16   303.1 1115.18   381.4 1096.95   459.6 1073.19
   518.2 1061.93   606.2  1055.9   684.5 1041.13   938.7  1029.5   987.6  1023.8
    1232 1023.07  1379.3 1018.29  1683.6 1018.88  1722.9 1015.61  1819.2 1019.04
  1905.8 1014.97    1925 1014.56  1927.6 1014.59  2195.8 1031.49  2302.8 1035.45
  2390.4 1047.43  2526.7 1058.91  2585.1 1068.25  2653.2 1083.27  2711.6 1099.44
  2760.2 1117.71  2779.7 1121.71  2818.6 1124.98  2847.8 1117.48  2867.3 1115.63
#Mann= 3 , 0 , 0
       0     .05       0  1905.8    .045       0  1927.6    .055       0
#XS Ineff= 2 , 0
         1684.53 1019.41
Permanent Ineff=
       F       F
Bank Sta=1905.8,1927.6
XS Rating Curve= 0 ,0
Exp/Cntr=0.3,0.1

Type RM Length L Ch R = 1 ,26039.7 ,904.7,895.9,885.9
XS GIS Cut Line= 4
     1811089.518      286095.462      1812717.99      285994.768
     1813099.584       285976.87     1813988.824      285911.434
#Sta/Elev= 30
       0 1237.55   186.8 1259.72   412.8 1267.18   570.1 1245.72   796.1 1253.51
  1071.3 1239.54  1110.7 1231.13  1169.6 1206.88  1258.1 1156.74  1307.2 1156.01
  1336.7 1140.91  1366.2 1137.63    1435 1143.71  1484.2 1134.21  1523.5 1120.33
  1690.4 1045.61  1729.5 1043.61  1798.1  1016.8  1827.5    1014  1886.3    1014
  1905.8    1014    2239 1023.23    2288 1036.05  2552.5 1076.96  2738.7 1116.27
    2817 1124.62  2846.4  1115.4  2875.8  1114.7  2885.6 1117.69  2905.2 1138.27
#Mann= 3 , 0 , 0
       0     .05       0  1886.3    .045       0  1905.8     .05       0
Bank Sta=1886.3,1905.8
XS Rating Curve= 0 ,0
Exp/Cntr=0.3,0.1

Type RM Length L Ch R = 1 ,25143.8 ,1819.1,1828.5,1828.2
XS GIS Cut Line= 3
      1812483.29      287128.492     1813399.344      286694.431
     1814087.456      286368.075
#Sta/Elev= 30
       0 1173.36    68.9 1153.24   137.8 1137.59   236.2 1111.75   403.5 1085.01
   639.7 1039.78   688.9 1032.84   718.4 1032.49   728.3 1030.49     748 1020.57
   757.8 1017.09   777.5 1015.57   925.1 1012.51     935  1012.2  937.81 1012.38
  1033.2 1018.47  1072.3 1025.46  1101.6 1027.65  1238.3 1043.79  1355.4 1052.82
  1404.2 1055.36  1511.6 1053.66  1550.7 1055.71  1609.3 1068.42    1619 1072.39
  1667.9 1103.64  1677.6 1109.08  1687.4 1112.68  1716.7  1113.9  1775.3 1107.38
#Mann= 3 , 0 , 0
       0     .05       0   925.1    .045       0  937.81     .05       0
Bank Sta=925.1,937.81
XS Rating Curve= 0 ,0
Exp/Cntr=0.3,0.1

Type RM Length L Ch R = 1 ,23315.4 ,1910.1,1918,1923.4
XS GIS Cut Line= 3
     1813093.257      288269.157     1813720.781      287979.771
     1814497.179      287614.603
#Sta/Elev= 30
       0 1196.09    29.2 1190.63    58.4    1182   107.1 1163.92   184.9 1133.22
   311.4 1088.36   369.8 1069.38   515.8  1028.1     545 1020.69   554.8 1020.05
     584  1024.2   603.4 1024.79   613.2 1023.38   632.6 1013.42   642.4 1010.99
   652.1  1010.8     661  1010.8   681.3 1011.35     808 1026.59   934.8 1039.64
   993.3 1043.97  1032.3 1048.21  1110.3 1059.51  1168.8 1065.58    1276 1079.87
  1373.5 1094.28  1412.5 1098.75    1510  1112.8  1529.5 1117.39    1549 1123.56
#Mann= 3 , 0 , 0
       0     .06       0   642.4    .045       0     661     .06       0
Bank Sta=642.4,661
XS Rating Curve= 0 ,0
Exp/Cntr=0.3,0.1

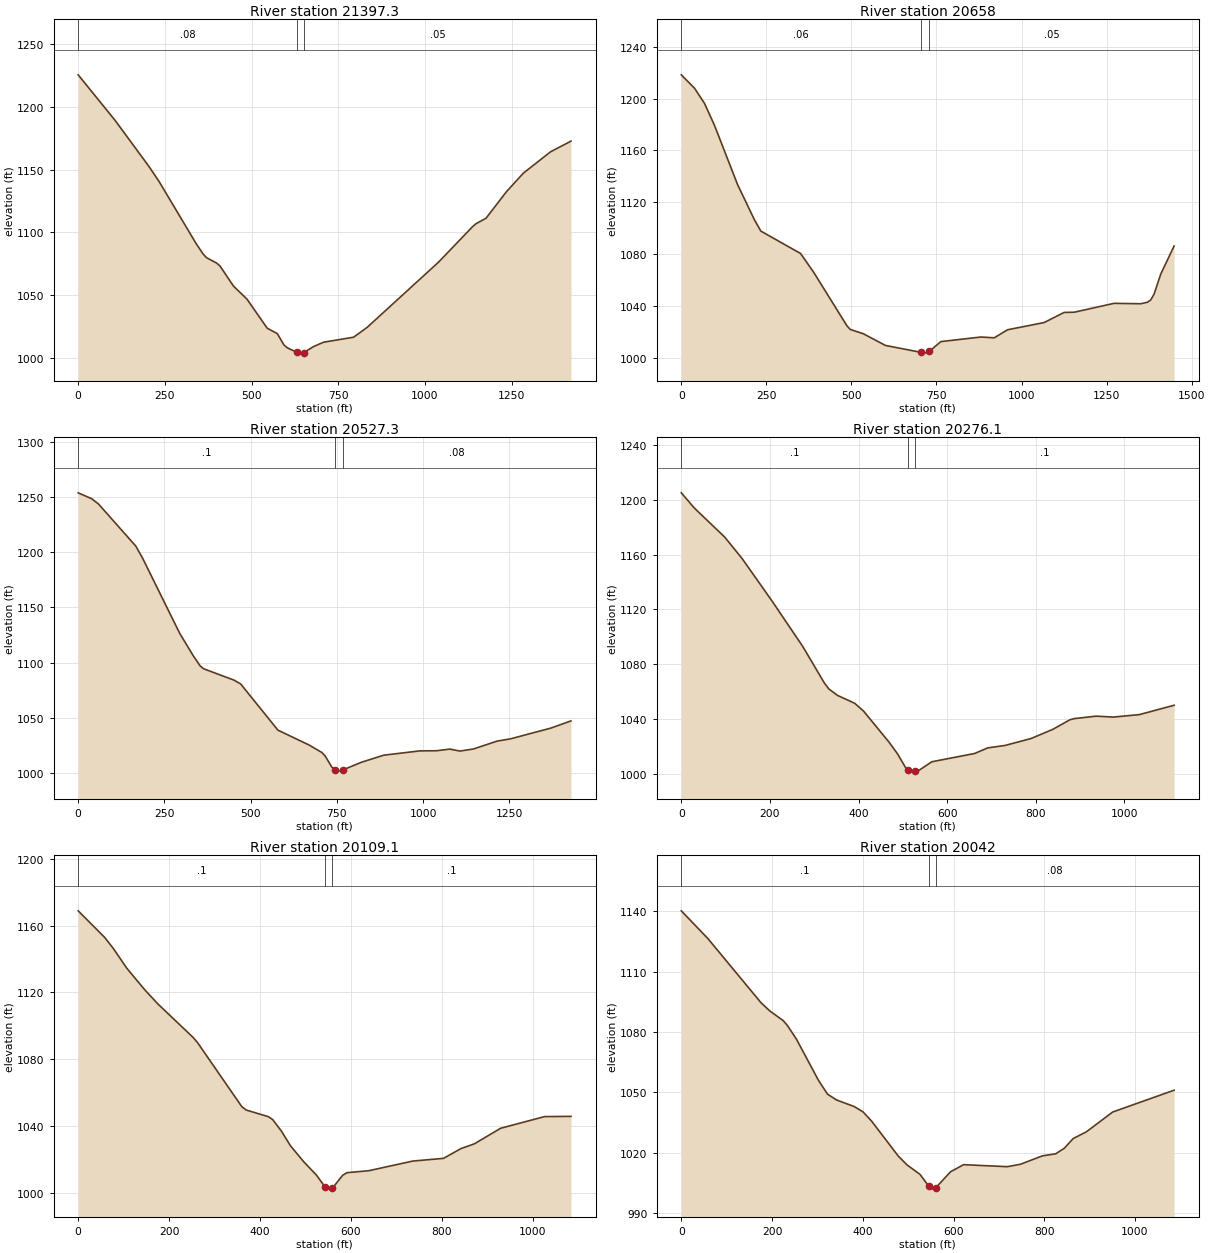
Type RM Length L Ch R = 1 ,21397.3 ,690.9,739.3,785.9
XS GIS Cut Line= 4
      1813733.29      289687.519     1814306.206      289645.853
      1814514.54      289618.075     1815149.956      289576.408
#Sta/Elev= 30
       0 1225.32   107.1 1188.89   204.5 1152.33   233.7 1140.35   340.8 1090.89
   360.2 1082.93     370 1079.99   399.2  1075.7   408.9  1073.4   447.9 1057.37
   486.8 1047.04   545.2 1023.88   574.4 1019.58   593.5 1010.56   603.1 1008.32
   631.8 1004.58   641.3 1004.06   650.7 1004.49   679.5 1009.35   708.2 1012.76
   794.4 1016.72   833.6 1024.55  1039.3 1076.36  1137.3 1104.54  1147.1 1106.88
  1176.5 1111.34  1235.2 1132.36  1284.2 1147.18  1362.6 1164.14  1421.4 1172.59
#Mann= 3 , 0 , 0
       0     .08       0   631.8    .045       0   650.7     .05       0
Bank Sta=631.8,650.7
XS Rating Curve= 0 ,0
Exp/Cntr=0.3,0.1

Type RM Length L Ch R = 1 ,20658   ,128.6,130.7,137.5
XS GIS Cut Line= 5
     1813784.679      289808.353     1814250.532      290030.349
     1814272.733      290187.354     1814204.818      290422.936
     1814597.179      290777.103
#Sta/Elev= 30
       0 1218.46      39 1208.06    68.2 1196.37    97.4 1179.52   165.5 1133.57
   214.2 1106.83   233.7 1097.71   350.5 1080.42   389.5  1065.7   486.8 1024.52
   496.6  1021.7   534.7 1018.42     600 1009.34     704 1004.03   713.8  1003.4
   728.9 1004.74   762.9 1012.31   880.6 1015.85   919.8 1015.23   958.9 1021.44
  1066.6 1027.05  1125.3 1034.86  1154.7    1035  1272.2 1041.89  1350.5 1041.56
    1370 1042.72  1379.8  1044.5  1389.6 1049.01  1409.2  1064.5  1448.4 1086.17
#Mann= 3 , 0 , 0
       0     .06       0     704    .045       0   728.9     .05       0
Bank Sta=704,728.9
XS Rating Curve= 0 ,0
Exp/Cntr=0.3,0.1

Type RM Length L Ch R = 1 ,20527.3 ,280.1,251.2,218.3
XS GIS Cut Line= 6
      1813639.54      289819.464     1814150.705      290091.112
      1814156.28      290199.363     1814126.018      290309.871
     1814107.563      290457.597      1814452.04      290788.214
#Sta/Elev= 30
       0 1253.82    39.2 1248.48    58.9 1243.69   166.8 1205.66   186.4 1194.83
   294.3 1126.54   333.6 1106.21   353.2 1097.18     363 1094.54   451.3 1084.22
   470.9 1080.71   578.9 1038.88   669.2 1025.41   706.4  1018.6   715.9  1015.4
     735 1005.47   744.6 1002.44   754.1 1001.75   767.5  1002.9   820.4 1009.73
   885.6 1016.19   989.7 1020.08  1038.4 1020.21  1077.4  1021.7  1106.6 1019.91
  1145.6 1021.82  1213.8  1028.9  1252.8 1030.98  1369.7  1040.7  1428.2 1047.24
#Mann= 3 , 0 , 0
       0      .1       0   744.6    .045       0   767.5     .08       0
Bank Sta=744.6,767.5
XS Rating Curve= 0 ,0
Exp/Cntr=0.3,0.1

Type RM Length L Ch R = 1 ,20276.1 ,184.2,167,149
XS GIS Cut Line= 4
     1813604.818      290065.644     1813883.463      290367.728
     1814052.734      290539.603     1814422.526       290813.04
#Sta/Elev= 30
       0 1205.13    29.4 1194.02    97.8 1172.83     137  1157.2   205.5 1125.71
     274  1092.9   322.9 1066.14   332.7 1061.88   352.3 1057.13   391.4 1051.31
     411 1045.74   468.9  1022.9   488.2 1014.26   507.5 1003.58   511.2 1002.87
   517.1 1001.75   526.8 1001.92   536.4 1002.33   565.4  1008.6     662 1014.64
   691.4 1018.72   730.5 1020.51   789.2 1025.57   838.1 1032.23   877.3 1039.33
     887 1040.13     936 1041.93   975.1 1041.25  1033.8 1043.06  1112.1 1049.89
#Mann= 3 , 0 , 0
       0      .1       0   511.2    .045       0   526.8      .1       0
Bank Sta=511.2,526.8
XS Rating Curve= 0 ,0
Exp/Cntr=0.3,0.1

Type RM Length L Ch R = 1 ,20109.1 ,66.4,67.1,67.6
XS GIS Cut Line= 4
     1813375.821      290323.824     1813774.088      290567.728
     1813945.963      290582.051     1814340.495       290787.78
#Sta/Elev= 30
       0 1168.83    58.4 1152.89    77.8  1146.1     107 1134.45   145.9 1121.71
   175.1 1113.13     253 1092.96   262.7 1089.88     360 1051.54   369.7  1049.5
   418.4 1045.53   428.1 1043.77   447.6  1036.7     467 1028.14   495.8 1018.67
   524.5 1010.45   543.7 1003.26   553.2 1002.11  558.62 1003.08   562.8 1003.81
     582 1010.41   591.6 1011.96   639.5 1013.14   736.2 1018.92   803.9 1020.54
   842.6 1026.43   871.6 1029.22   929.7 1038.57  1026.4 1045.57  1084.4 1045.69
#Mann= 3 , 0 , 0
       0      .1       0   543.7    .045       0  558.62      .1       0
Bank Sta=543.7,558.62
XS Rating Curve= 0 ,0
Exp/Cntr=0.3,0.1

Type RM Length L Ch R = 1 ,20042   ,441.2,459.2,477.6
XS GIS Cut Line= 4
     1813334.155      290379.379     1813735.026      290622.415
     1813906.901      290636.738     1814301.432      290842.467
#Sta/Elev= 30
       0 1140.19    58.6 1126.41   175.8 1094.52   195.3 1090.43   224.6 1085.68
   234.4 1083.06   253.9 1076.41   302.8 1055.82   322.3 1049.15   341.8 1046.28
   380.9 1043.01   400.4 1040.38     420  1035.6   478.4 1018.34   497.5 1014.01
   526.3 1009.26   545.4  1003.4     555 1001.97  560.73 1002.62   593.4 1010.58
   622.1 1014.11   718.6 1013.12   747.7 1014.33     796  1018.5     825 1019.48
   844.4 1022.31   863.7 1027.08   892.8 1030.43   950.8 1040.26  1086.2  1051.1
#Mann= 3 , 0 , 0
       0      .1       0   545.4    .045       0  560.73     .08       0
Bank Sta=545.4,560.73
XS Rating Curve= 0 ,0
Exp/Cntr=0.3,0.1

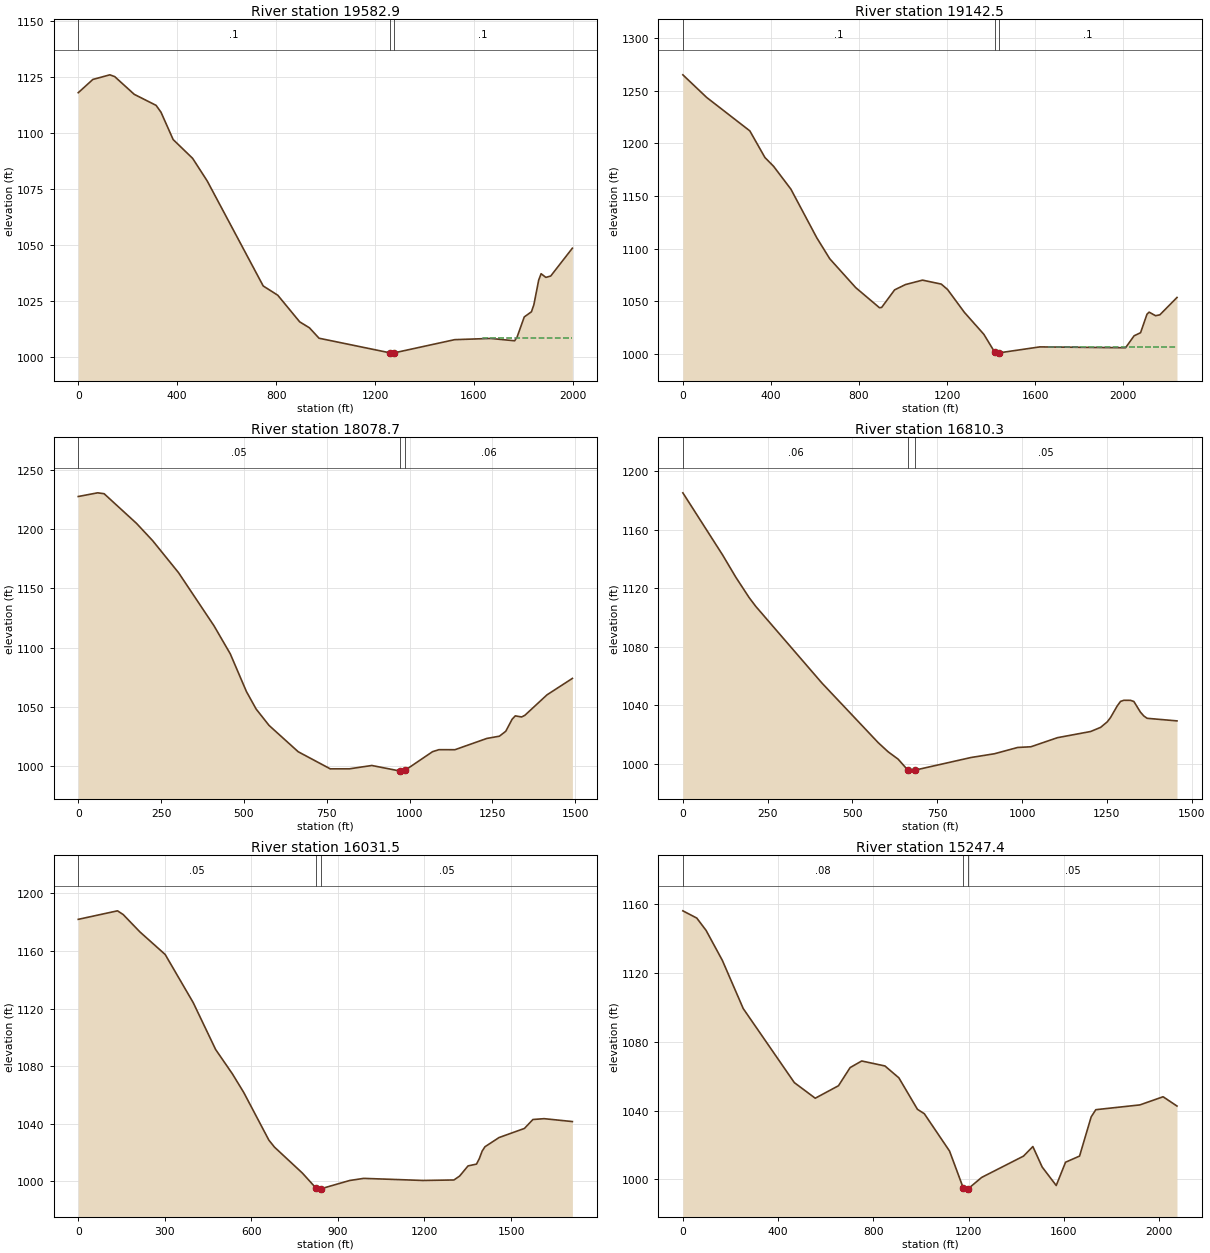
Type RM Length L Ch R = 1 ,19582.9 ,454,440.3,419.6
XS GIS Cut Line= 5
     1812589.193      290091.686     1813294.181      290720.265
     1813555.899       291017.14     1813753.816      291112.192
     1814191.316      291129.119
#Sta/Elev= 30
       0 1117.81      59 1123.72   127.9 1125.79   147.6 1124.98   226.3 1117.09
   314.8 1112.16   334.5 1109.11   383.7  1096.9   462.4 1088.51   521.4 1078.42
   747.8 1031.55   806.8  1027.4   895.3 1015.53   934.7 1012.87   973.5 1008.22
  1260.6 1001.69  1272.7 1001.57  1275.6 1001.65  1521.7 1007.58  1666.9 1008.13
  1764.2 1007.08  1773.9 1008.66  1803.1 1017.71  1832.3 1020.04    1842 1023.18
  1861.5 1034.16  1871.2 1037.01  1890.6 1035.38  1910.1 1035.98  1997.7 1048.41
#Mann= 3 , 0 , 0
       0      .1       0  1260.6    .045       0  1275.6      .1       0
#XS Ineff= 2 , 0
                          1637.5         1008.15
Permanent Ineff=
       F       F
Bank Sta=1260.6,1275.6
XS Rating Curve= 0 ,0
Exp/Cntr=0.3,0.1

Type RM Length L Ch R = 1 ,19142.5 ,1071.3,1063.8,1054.7
XS GIS Cut Line= 5
     1811940.755      291221.894     1813000.651      291247.936
     1813188.151      291276.582     1813511.068      291266.165
     1814182.635      291244.136
#Sta/Elev= 30
       0 1265.28     108 1243.79   304.3 1211.94     373 1186.55   412.3 1178.22
   490.8  1156.5   608.6 1110.16   667.5 1090.22   785.3  1062.8   893.3 1043.66
   903.2 1043.96     962 1060.65  1011.1 1065.68  1088.7 1069.92    1174 1066.15
  1202.5 1061.02  1279.3 1039.18  1367.4 1018.38  1416.3 1001.54  1426.1 1000.46
  1435.9  1000.7  1621.7 1006.39  2011.2 1005.55  2050.1 1016.95  2079.4 1019.87
  2108.6  1037.5  2118.3 1039.46  2147.5 1036.05    2167  1036.9  2244.9  1053.4
#Mann= 3 , 0 , 0
       0      .1       0  1416.3    .045       0  1435.9      .1       0
#XS Ineff= 2 , 0
                         1660.69         1006.55
Permanent Ineff=
       F       F
Bank Sta=1416.3,1435.9
XS Rating Curve= 0 ,0
Exp/Cntr=0.3,0.1

Type RM Length L Ch R = 1 ,18078.7 ,1247,1268.4,1288.2
XS GIS Cut Line= 4
     1812836.588      292181.096     1813527.561       292125.54
     1813961.588      291993.596     1814291.449      291892.901
#Sta/Elev= 30
       0 1227.46    58.6 1230.57    78.1 1229.82   175.7 1204.86   224.6 1190.23
   302.7 1163.27   410.1 1118.32   458.9 1094.82   507.7 1063.01     537 1048.25
     576 1034.44   663.9 1012.26   760.8  997.81   818.7  997.83   886.2 1000.65
   972.1  995.93   973.1  995.89   987.1  996.69  1069.6  1012.3  1088.9 1013.98
  1137.2 1013.95  1233.1 1023.43  1271.4 1025.36  1290.6 1029.49  1309.7 1039.62
  1319.3 1042.49  1338.4 1041.58    1348  1042.9  1415.1 1060.22  1491.7 1074.08
#Mann= 3 , 0 , 0
       0     .05       0   972.1    .045       0   987.1     .06       0
Bank Sta=972.1,987.1
XS Rating Curve= 0 ,0
Exp/Cntr=0.3,0.1

Type RM Length L Ch R = 1 ,16810.3 ,796.2,778.8,761.6
XS GIS Cut Line= 3
     1812756.111      292498.522     1813266.765      292922.985
     1813904.907      293393.359
#Sta/Elev= 30
       0 1185.27   117.2 1142.76   156.2 1127.52   195.3 1113.64   214.8 1107.63
   410.1 1055.12   576.1 1014.32   605.4 1008.06   634.7 1003.07     664   995.4
   673.8  994.88   683.6  995.52     850 1004.22   918.5 1006.76     987 1011.06
  1026.2 1011.55  1104.4 1017.76  1202.3 1021.99  1231.7 1024.83  1251.3 1028.61
    1261 1031.58  1280.6 1039.49  1290.4 1042.58  1300.2 1043.34  1319.8 1043.31
  1329.6 1042.54  1349.1 1035.21  1358.9 1032.64  1368.7 1031.02  1456.8 1029.25
#Mann= 3 , 0 , 0
       0     .06       0     664    .045       0   683.6     .05       0
Bank Sta=664,683.6
XS Rating Curve= 0 ,0
Exp/Cntr=0.3,0.1

Type RM Length L Ch R = 1 ,16031.5 ,811.8,784.1,757.2
XS GIS Cut Line= 4
     1812120.009      293687.606     1812786.241      293611.651
      1813083.55      293576.929     1813821.397      293492.294
#Sta/Elev= 30
       0 1181.96     136 1187.88   155.5 1185.34   213.8 1173.22   301.3 1157.55
   398.4 1124.13   476.2 1091.54   534.5 1074.55   573.4 1061.77   660.8 1028.56
   680.2 1023.71   776.8 1005.71  823.48  995.39   834.7  994.55  840.57  994.77
   940.9 1000.55   989.4 1002.02  1194.6 1000.57  1302.1 1000.91  1321.7 1003.61
    1351 1010.68  1380.3 1011.93  1390.1 1015.76  1399.8 1020.95  1409.6 1023.99
  1458.5 1030.39  1546.4 1036.71  1575.8 1042.92  1614.8 1043.49  1712.6 1041.49
#Mann= 3 , 0 , 0
       0     .05       0  823.48    .045       0  840.57     .05       0
Bank Sta=823.48,840.57
XS Rating Curve= 0 ,0
Exp/Cntr=0.3,0.1

Type RM Length L Ch R = 1 ,15247.4 ,197,198.4,198.7
XS GIS Cut Line= 5
     1812447.699      295024.412      1813233.29      294429.794
     1813356.988      294147.676     1813549.714      293817.226
     1813798.412      293504.726
#Sta/Elev= 30
       0 1156.17    58.5 1151.96    97.6 1144.79   165.8 1127.38   253.6 1099.34
   468.2  1056.3     556 1047.23   653.6 1054.49   702.4 1065.03   751.1 1068.88
   848.7 1065.98   907.2 1059.08   985.2 1040.78  1014.1 1038.22    1120 1016.51
  1177.8     995  1187.4  994.38    1197  994.46  1254.8 1001.18  1430.6 1013.57
  1469.9 1019.14  1509.1 1007.21    1568   996.5  1607.2 1010.02    1666 1013.59
  1714.8 1036.39  1734.3 1040.56  1919.4 1043.34  2016.8 1048.08  2075.2 1042.68
#Mann= 3 , 0 , 0
       0     .08       0  1177.8    .045       0    1197     .05       0
#XS Ineff= 2 , 0
                         1351.49         1007.91
Permanent Ineff=
       F       F
Bank Sta=1177.8,1197
XS Rating Curve= 0 ,0
Exp/Cntr=0.3,0.1