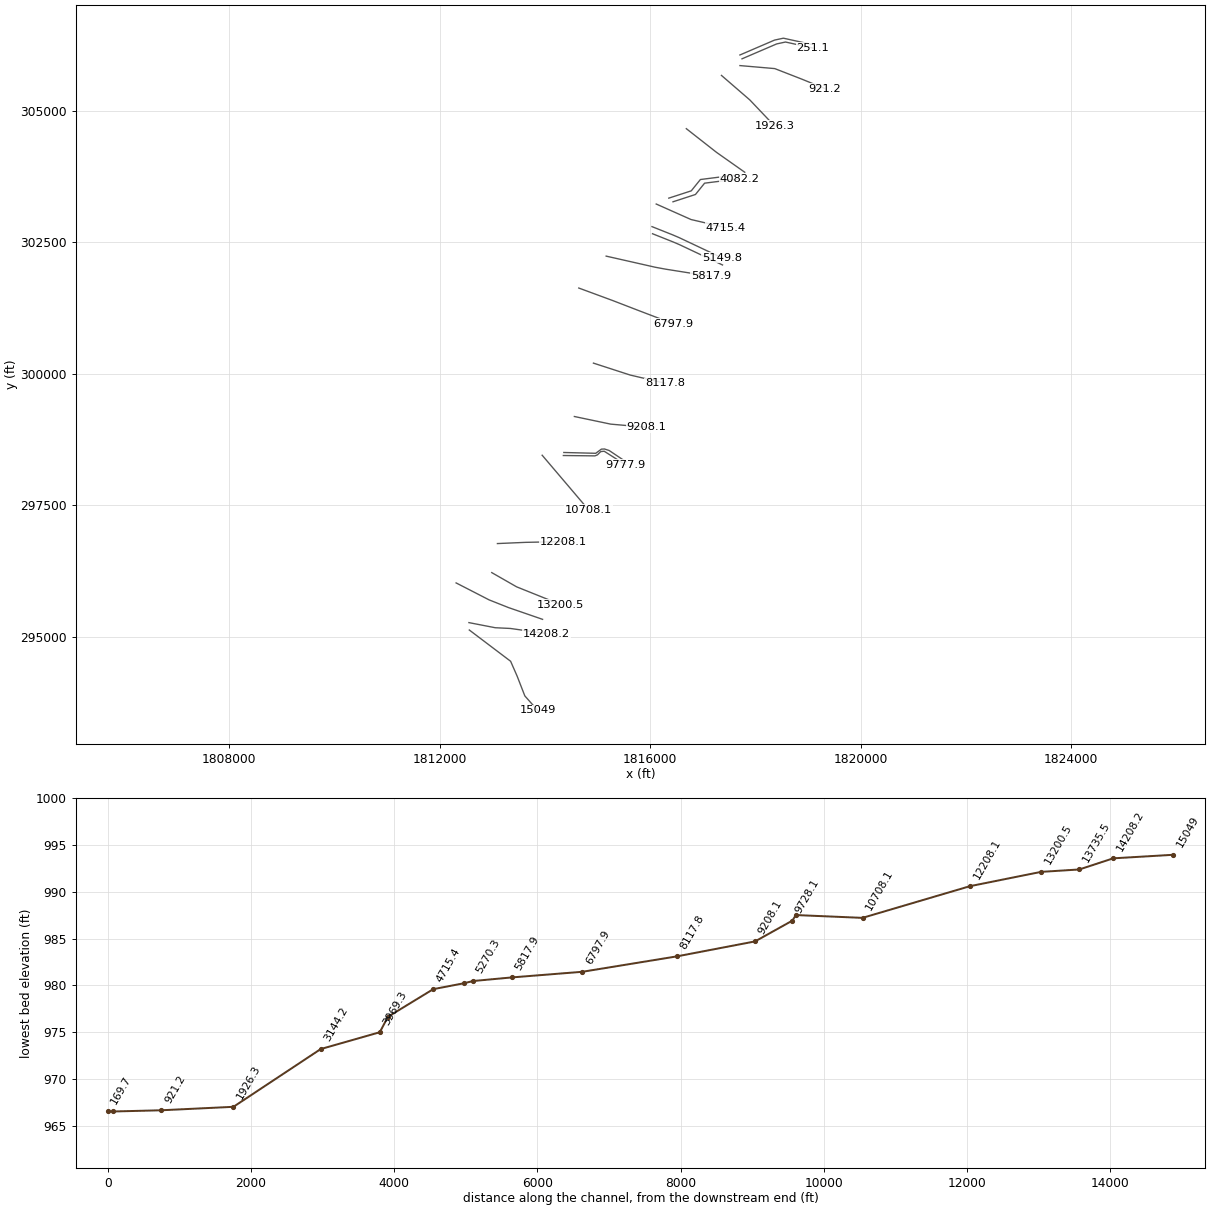
HEC-RAS study BerkeleyRn.prj: BerkeleyRn

--- BerkeleyRn.g01 (geometry) --- (continued)

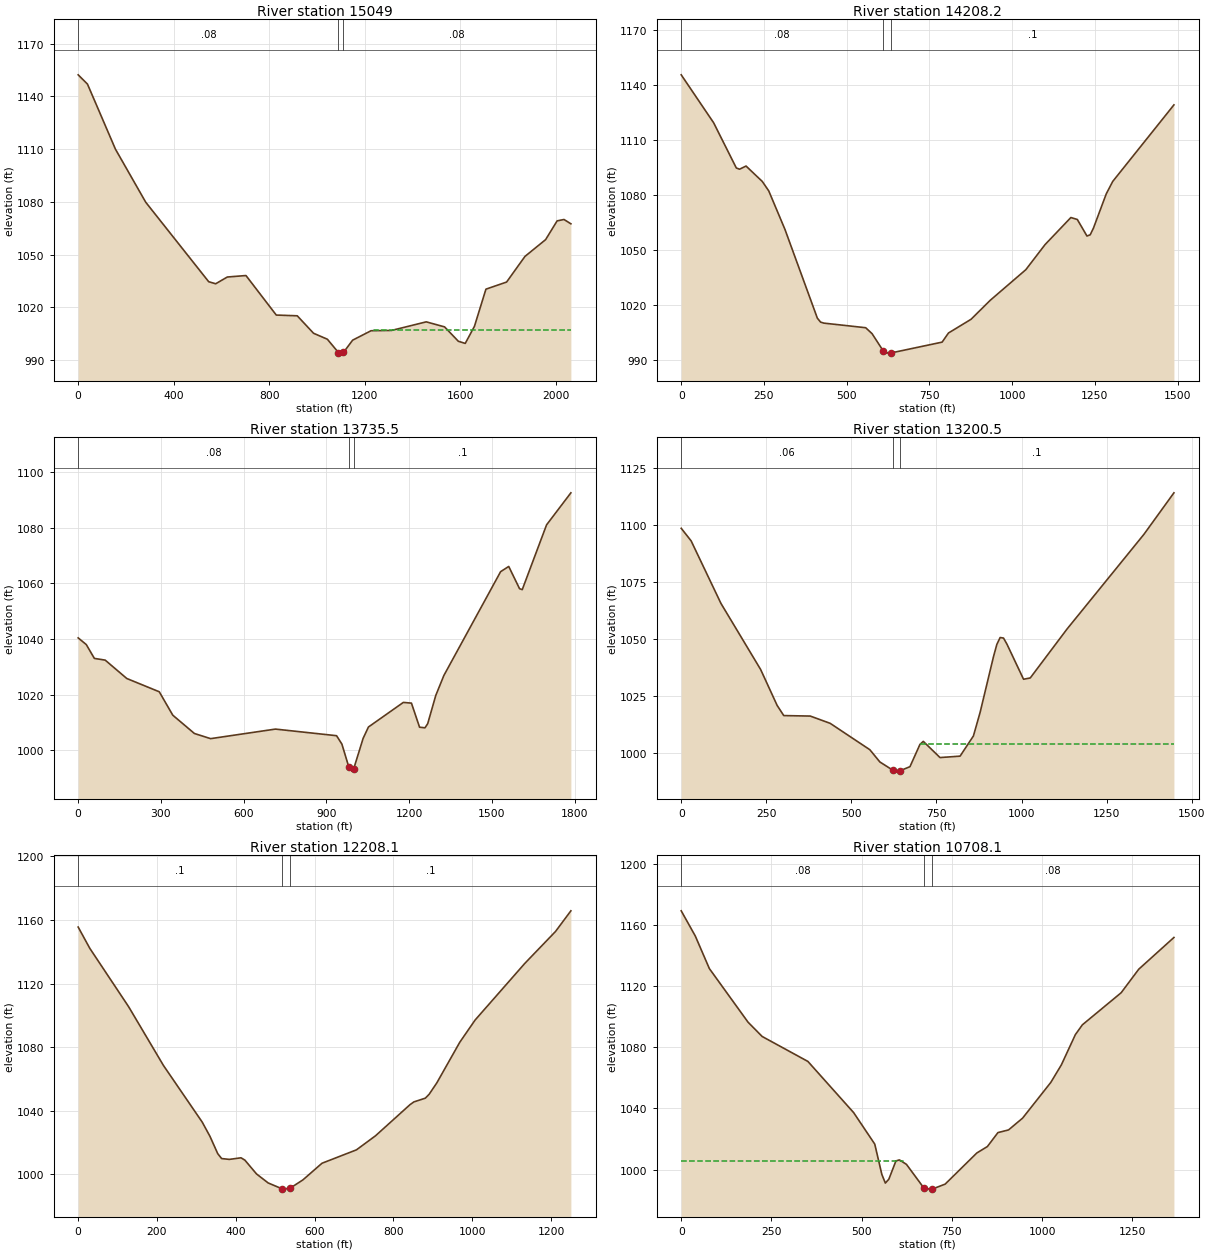
Type RM Length L Ch R = 1 ,15049   ,812.9,840.8,868.6
XS GIS Cut Line= 5
     1812560.547      295126.408     1813346.137       294531.79
     1813469.835      294249.672     1813616.121      293873.216
     1813858.308      293599.779
#Sta/Elev= 30
       0 1152.26      39 1146.97   156.1 1109.95   282.9 1079.77   546.3 1034.59
   575.5 1033.42   624.3 1037.26   702.4  1038.1   829.2 1015.62     917  1015.2
   985.2 1005.27    1043 1001.88 1089.61  994.28  1100.8  993.97  1110.4  994.35
  1148.9 1001.35  1225.9  1006.7  1312.5 1006.89  1456.8 1011.76  1533.7  1008.9
  1591.4 1000.71  1620.2   999.5  1658.7 1009.21  1706.8 1030.35  1793.3  1034.4
  1870.2 1048.98  1956.7 1058.53  2004.8  1069.2  2033.6 1069.98  2062.4 1067.53
#Mann= 3 , 0 , 0
       0     .08       0 1089.61    .045       0  1110.4     .08       0
#XS Ineff= 2 , 0
                         1236.28         1006.97
Permanent Ineff=
       F       F
Bank Sta=1089.61,1110.4
XS Rating Curve= 0 ,0
Exp/Cntr=0.3,0.1

Type RM Length L Ch R = 1 ,14208.2 ,479.6,472.7,464.8
XS GIS Cut Line= 4
     1812553.747      295266.889     1813053.747      295169.666
     1813341.941      295155.777     1814025.969      295058.555
#Sta/Elev= 30
       0 1145.33      98 1119.18   166.5 1094.55   176.3 1093.87   195.9 1095.59
   244.9  1087.2   264.5 1082.06   313.5 1061.03   411.4 1012.64   421.2  1010.5
     431 1009.95   557.4 1007.44   576.7  1004.2  610.75  994.71   624.8  993.59
   634.4  993.71   788.3  999.58   807.6 1004.56   875.7 1012.03   934.1 1022.45
  1041.2 1039.07  1099.6  1052.8  1177.4 1067.52  1196.9 1066.46  1226.1 1057.43
  1235.8 1058.11  1245.5  1061.7  1284.4 1080.46  1303.9 1087.21  1488.8 1128.94
#Mann= 3 , 0 , 0
       0     .08       0  610.75    .045       0   634.4      .1       0
Bank Sta=610.75,634.4
XS Rating Curve= 0 ,0
Exp/Cntr=0.3,0.1

Type RM Length L Ch R = 1 ,13735.5 ,535.6,535,532.8
XS GIS Cut Line= 4
      1812310.26      296021.925     1812937.864      295699.009
     1813305.051      295553.175     1813953.489      295329.217
#Sta/Elev= 30
       0 1040.39    29.4 1037.98    58.8    1033      98 1032.38   176.4 1025.76
   294.1 1020.98   343.1 1012.55   421.5 1005.96   480.3  1004.1   715.4 1007.54
   937.1 1005.16   956.4 1002.14  981.53  993.89   994.9   992.4   999.5  993.32
  1033.4 1004.19  1052.7 1008.29  1179.3 1017.15  1208.7 1016.89  1238.1 1008.22
  1257.7    1008  1267.5 1009.47  1296.9 1019.66  1326.3 1026.86  1532.1 1064.25
  1561.5 1066.12  1600.7 1058.12  1610.5 1057.77  1698.7  1081.1  1786.9 1092.64
#Mann= 3 , 0 , 0
       0     .08       0  981.53    .045       0   999.5      .1       0
Bank Sta=981.53,999.5
XS Rating Curve= 0 ,0
Exp/Cntr=0.3,0.1

Type RM Length L Ch R = 1 ,13200.5 ,980,992.4,1000.2
XS GIS Cut Line= 3
     1812987.475      296218.027     1813459.997      295947.444
     1814298.157      295610.356
#Sta/Elev= 30
       0 1098.47    29.2 1092.95   116.7 1065.59   233.4 1036.64     282 1020.88
   301.4 1016.46   379.2 1016.25   437.6 1013.08   554.3 1001.52   583.8  996.15
   623.1  992.44   632.9  992.14   642.7  992.29   672.2  994.09   701.6 1003.85
   711.4 1005.17   760.5  998.08   819.5   998.7   858.7 1007.55   878.4 1017.89
   917.7 1042.29   927.5 1047.62   937.3 1050.65   947.1  1050.4   956.9 1047.84
    1006 1032.37  1025.7 1032.94  1133.7 1054.34  1359.5 1095.78  1447.9    1114
#Mann= 3 , 0 , 0
       0     .06       0   623.1    .045       0   642.7      .1       0
#XS Ineff= 2 , 0
                          701.76         1003.91
Permanent Ineff=
       F       F
Bank Sta=623.1,642.7
XS Rating Curve= 0 ,0
Exp/Cntr=0.3,0.1

Type RM Length L Ch R = 1 ,12208.1 ,1519.1,1500,1479.5
XS GIS Cut Line= 3
     1813095.414      296770.361     1813626.265      296793.226
     1814345.233      296808.096
#Sta/Elev= 30
       0 1155.58    29.5  1142.2   127.9  1105.5   216.5 1068.43   314.9 1032.77
   334.6 1023.78   354.2 1012.94   364.1 1009.85   383.8 1009.33   413.3 1010.33
   423.1 1008.86   452.6 1000.18   482.2   994.5  517.44  990.81   521.5  990.61
   538.8  991.35   570.2  996.39   618.8  1006.9   706.3 1015.34   754.8 1024.22
   842.3  1043.8     852 1045.51   881.2 1047.88   890.9 1050.37   910.3 1057.52
   968.6  1083.1  1007.5 1097.08  1133.8 1132.77  1211.6 1152.83  1250.5  1165.8
#Mann= 3 , 0 , 0
       0      .1       0  517.44    .045       0   538.8      .1       0
Bank Sta=517.44,538.8
XS Rating Curve= 0 ,0
Exp/Cntr=0.3,0.1

Type RM Length L Ch R = 1 ,10708.1 ,904.8,930.2,954
XS GIS Cut Line= 3
     1813945.685      298450.338     1814387.626      297930.248
     1814829.568      297410.157
#Sta/Elev= 30
       0 1169.08      39 1152.63      78 1131.34   185.2  1096.3   224.2 1086.98
     351 1070.66   477.8 1037.19   536.2 1016.64   555.8  996.86   565.5  991.17
   575.2  993.69   594.8 1005.64   604.5 1006.32     624 1003.41   672.8  987.78
   692.2  987.22  696.12  987.32   731.2  990.49     819 1010.85   848.2 1015.04
   877.5 1024.17   906.8  1025.9   945.8 1033.62  1023.8 1056.92    1053 1068.34
    1092 1088.21  1111.5 1094.62  1218.8 1115.55  1267.5 1130.91    1365 1151.67
#Mann= 3 , 0 , 0
       0     .08       0   672.8    .045       0  696.12     .08       0
#XS Ineff= 2 , 0
          614.55 1005.29
Permanent Ineff=
       F       F
Bank Sta=672.8,696.12
XS Rating Curve= 0 ,0
Exp/Cntr=0.3,0.1

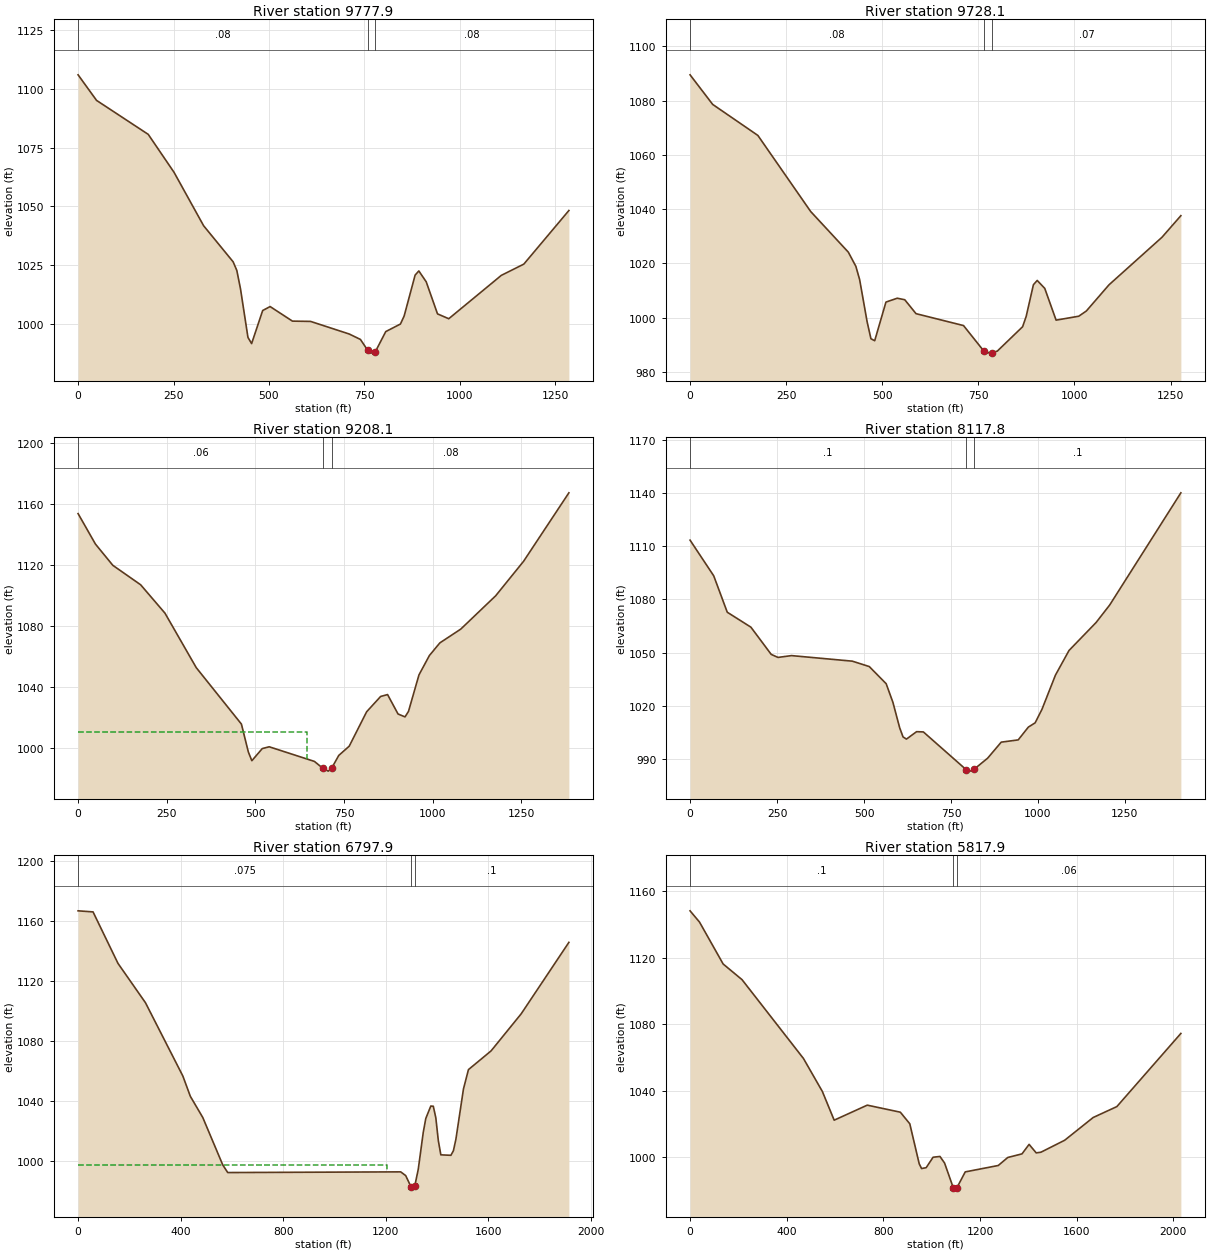
Type RM Length L Ch R = 1 ,9777.9  ,54.1,49.8,46.2
XS GIS Cut Line= 6
     1814348.651      298444.776     1814949.004      298438.158
     1814995.879      298457.255     1815058.721      298519.429
     1815124.693      298526.373     1815528.976      298269.024
#Sta/Elev= 30
       0 1106.05    48.4 1095.16   183.8 1080.69   251.5  1064.5   328.9 1041.77
   406.3 1026.39   415.9 1022.71   425.6 1014.81     445  994.24   454.6  991.57
   483.6 1005.66   503.1 1007.35   561.6 1001.15   609.1 1001.03   710.2  995.67
   739.7  993.35   758.7  988.74   768.1  987.52   778.7  988.09     806  996.69
   844.5  999.91   854.2 1003.32     883 1020.76   892.7 1022.52   912.1 1017.88
   941.6 1004.24   971.1 1002.17  1108.8 1020.64  1167.8 1025.44  1285.8 1048.26
#Mann= 3 , 0 , 0
       0     .08       0   758.7    .045       0   778.7     .08       0
#XS Ineff= 2 , 0
          609.06 1000.92
Permanent Ineff=
       F       F
Bank Sta=758.7,778.7
XS Rating Curve= 0 ,0
Exp/Cntr=0.3,0.1

Type RM Length L Ch R = 1 ,9728.1  ,525.2,520,516.8
XS GIS Cut Line= 6
     1814357.332      298502.545      1814963.98      298487.166
     1815071.381      298566.376     1815129.715      298569.154
      1815219.08      298540.334     1815537.656      298326.793
#Sta/Elev= 30
       0 1089.51    58.8 1078.61   176.4 1067.17   313.7 1039.14   411.7 1024.14
   431.3 1018.92   441.1 1014.04   460.7   998.4   470.5  992.23   480.3  991.49
   509.6 1005.74     539 1007.16   558.5  1006.6   587.8 1001.47   711.4  997.08
  763.38  987.83   779.9  986.92     785  987.05   799.3  987.67   865.1  996.65
   874.4 1000.47   893.2 1012.14   903.1 1013.71   922.7 1010.79   952.2  999.08
  1011.2 1000.53  1030.9 1002.45  1089.9 1012.11  1227.6 1029.62  1276.8 1037.59
#Mann= 3 , 0 , 0
       0     .08       0  763.38    .045       0     785     .07       0
#XS Ineff= 2 , 0
          627.63   999.8
Permanent Ineff=
       F       F
Bank Sta=763.38,785
XS Rating Curve= 0 ,0
Exp/Cntr=0.3,0.1

Type RM Length L Ch R = 1 ,9208.1  ,1090.6,1090.3,1086.8
XS GIS Cut Line= 3
     1814558.035      299186.848     1815248.548      299041.833
     1815924.379      298982.535
#Sta/Elev= 30
       0 1153.78      49 1133.76      98 1119.82   176.4 1107.06     245 1088.42
   333.2 1052.64   460.6 1015.58   480.2  997.22     490  991.53   519.4  999.51
     539 1000.68   666.4  991.08  690.17  986.58   705.6   984.7   715.4  986.77
   735.1  995.01   764.6 1001.09   813.7 1023.67   853.1 1033.71   872.7 1034.97
   902.2 1022.22   921.9 1020.31   931.7  1023.9   961.2 1047.85   990.7 1060.61
  1020.2  1068.9  1079.2 1077.96  1177.5 1099.81  1256.2 1122.46    1384 1167.42
#Mann= 3 , 0 , 0
       0     .06       0  690.17    .045       0   715.4     .08       0
#XS Ineff= 2 , 0
          646.29 1010.41
Permanent Ineff=
       F       F
Bank Sta=690.17,715.4
XS Rating Curve= 0 ,0
Exp/Cntr=0.3,0.1

Type RM Length L Ch R = 1 ,8117.8  ,1321.5,1319.8,1317
XS GIS Cut Line= 3
     1814920.174      300202.008     1815622.721       299974.11
     1816277.338      299821.475
#Sta/Elev= 30
       0 1113.42      68  1093.3   106.9 1072.76   174.9 1064.32   233.2 1048.98
   252.7 1047.25   291.6 1048.28   466.5 1045.14   515.1  1042.1   563.7 1032.42
   583.1  1021.9   602.5 1007.55   612.2 1002.39     622 1001.17   651.1 1005.36
   670.6 1005.22  794.37  983.81   806.8   983.1   816.5  984.18   855.5  990.43
   894.4  999.45   943.2 1000.72   972.4 1007.94   991.9 1010.35  1011.4 1017.92
  1050.3 1037.28  1089.3 1051.18  1167.2 1066.97  1206.2 1076.83  1410.8 1140.12
#Mann= 3 , 0 , 0
       0      .1       0  794.37    .045       0   816.5      .1       0
Bank Sta=794.37,816.5
XS Rating Curve= 0 ,0
Exp/Cntr=0.3,0.1

Type RM Length L Ch R = 1 ,6797.9  ,975.4,980.1,984.1
XS GIS Cut Line= 4
     1814641.423      301630.252     1815280.449      301394.497
     1815800.744      301193.643     1816432.112      300952.867
#Sta/Elev= 30
       0 1167.03    58.4 1166.31   155.7 1131.97   262.7  1105.8   408.7 1056.88
   437.9 1043.34   486.5  1029.2   564.4  997.59   583.8   992.5  1258.4  992.96
    1278  990.47  1298.5  983.07  1307.4  981.45  1313.5  983.59    1327  994.67
  1346.6 1019.41  1356.4 1028.56    1376 1036.86  1385.7 1036.71  1395.5 1029.04
  1405.3 1013.79  1415.1 1004.32  1454.3    1004  1464.1 1007.05  1473.9 1014.76
  1503.3 1048.22  1522.8 1061.14    1611 1073.62  1728.5 1098.35  1914.6    1146
#Mann= 3 , 0 , 0
       0    .075       0  1298.5    .045       0  1313.5      .1       0
#XS Ineff= 2 , 0
         1203.83  997.46
Permanent Ineff=
       F       F
Bank Sta=1298.5,1313.5
XS Rating Curve= 0 ,0
Exp/Cntr=0.3,0.1

Type RM Length L Ch R = 1 ,5817.9  ,551.6,547.5,541.6
XS GIS Cut Line= 4
     1815162.025       302237.08       1816096.4       302025.39
      1816292.58      301988.932     1817155.101      301852.185
#Sta/Elev= 30
       0 1148.04    39.1 1141.28   136.9  1116.1   215.1 1106.68   469.2 1059.34
   547.5  1039.5   596.3 1022.27   733.2  1031.3   870.1 1027.07   909.2  1020.1
   948.3  996.02     958  993.21   977.1  993.75  1005.6 1000.02  1034.1 1000.47
  1053.1  996.52  1089.3  981.59  1100.6  980.85  1104.3  981.73  1138.6   991.2
  1275.3  995.05  1314.6  999.86  1373.5 1002.03  1402.9 1007.73  1432.3 1002.62
    1452 1003.04  1550.1 1010.21  1667.8 1023.86    1766 1030.43  2030.9 1074.38
#Mann= 3 , 0 , 0
       0      .1       0  1089.3    .045       0  1104.3     .06       0
Bank Sta=1089.3,1104.3
XS Rating Curve= 0 ,0
Exp/Cntr=0.3,0.1

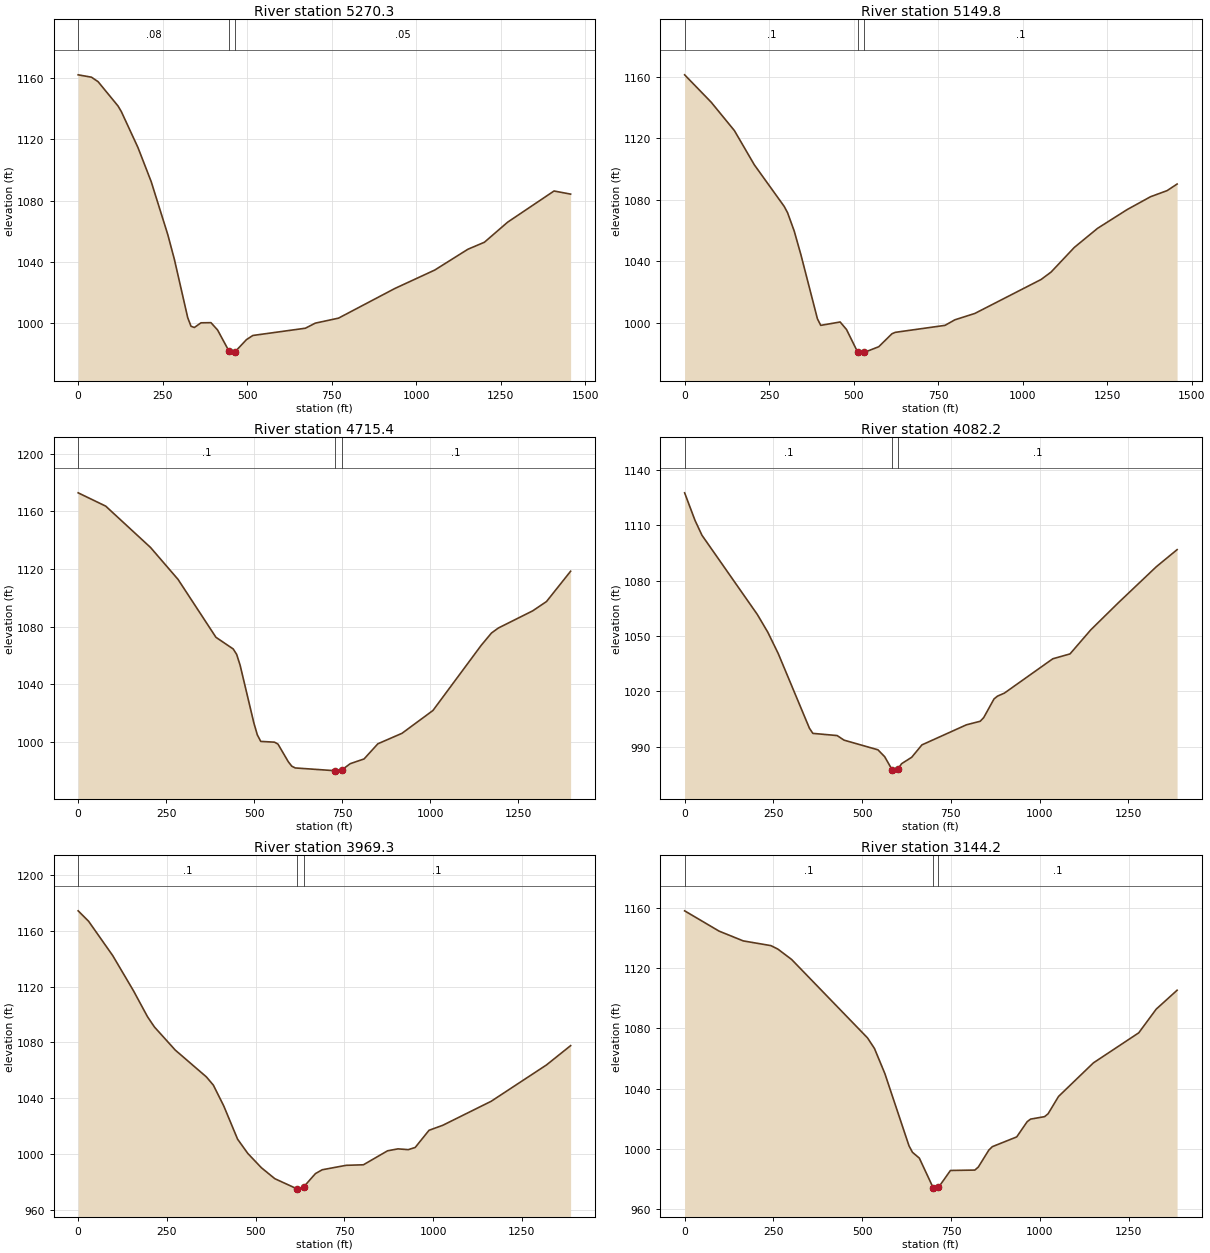
Type RM Length L Ch R = 1 ,5270.3  ,120.7,120.6,120.7
XS GIS Cut Line= 4
      1816043.33      302662.722     1816435.691      302506.472
     1816557.219      302454.389     1817373.191      302068.972
#Sta/Elev= 30
       0 1162.08    39.3 1160.54    58.9 1157.62   117.9 1141.76   127.7 1138.11
   176.8 1114.69   216.1 1092.36   265.2 1057.78   284.8 1041.54   324.1 1003.64
   333.9  997.99   343.8  997.19   363.4 1000.24   392.9 1000.34   412.5  995.55
  446.46  981.67   450.7  980.46   464.2  981.36   497.9  989.26   516.8  991.98
   672.2  996.71   701.7 1000.03   770.3 1003.29   937.1 1022.66  1054.8 1034.65
  1152.9 1048.23  1201.9 1052.82  1270.6 1065.91  1407.9 1086.27    1457 1084.23
#Mann= 3 , 0 , 0
       0     .08       0  446.46    .045       0   464.2     .05       0
Bank Sta=446.46,464.2
XS Rating Curve= 0 ,0
Exp/Cntr=0.3,0.1

Type RM Length L Ch R = 1 ,5149.8  ,431.3,434.4,438.1
XS GIS Cut Line= 4
     1816032.914      302798.139     1816425.275      302641.889
     1816546.802      302589.805     1817362.775      302204.389
#Sta/Elev= 30
       0 1161.17    78.6 1143.36   147.3  1124.9   206.2 1102.67   294.6 1075.62
   304.5 1071.54   324.1 1059.69   343.8  1044.4   392.9 1002.55   402.7  998.27
   460.1 1000.48     479  995.57   507.3  982.95  513.85  981.16   526.2  980.23
   531.2  980.68   574.2  984.38   613.4  992.82   623.2  993.74   770.3  998.28
   799.8 1001.91   858.6 1006.02  1054.8 1028.13  1084.2 1032.94  1152.9 1048.94
  1221.6 1061.35  1309.8 1073.63  1378.5 1081.92  1427.5 1085.89    1457 1090.16
#Mann= 3 , 0 , 0
       0      .1       0  513.85    .045       0   531.2      .1       0
Bank Sta=513.85,531.2
XS Rating Curve= 0 ,0
Exp/Cntr=0.3,0.1

Type RM Length L Ch R = 1 ,4715.4  ,605.9,633.2,658.5
XS GIS Cut Line= 3
     1816113.691      303227.968     1816775.401      302932.962
     1817432.807      302779.676
#Sta/Elev= 30
       0 1172.82    78.3 1163.58   205.6  1134.9   283.9 1112.69   391.6  1072.5
   440.6 1064.41   450.4 1060.66   460.2 1053.17   499.3 1013.08   509.1 1004.81
   518.9 1000.22     558   999.7   567.8  998.37   597.2   986.1     607  983.03
   616.8   981.8  730.77  979.86   734.3  979.59   748.4   980.3   773.4  984.79
   812.5  988.04   851.7  998.57   920.2 1005.84  1008.2 1021.68  1145.2 1066.87
  1174.5 1075.46  1194.1 1078.95  1291.9  1090.9    1331 1097.35  1399.5 1118.39
#Mann= 3 , 0 , 0
       0      .1       0  730.77    .045       0   748.4      .1       0
Bank Sta=730.77,748.4
XS Rating Curve= 0 ,0
Exp/Cntr=0.3,0.1

Type RM Length L Ch R = 1 ,4082.2  ,112.8,112.9,113.3
XS GIS Cut Line= 4
     1816432.219      303270.361     1816859.302       303409.25
     1817032.914      303624.527     1817689.164      303707.861
#Sta/Elev= 30
       0 1127.74    29.3 1112.76    48.8 1104.71     205 1061.63   234.3 1052.05
   263.6  1040.5   351.5  999.95   361.2  997.13   429.6  995.94   449.1  993.45
   544.5  988.21   563.5  984.47   584.5  977.36   592.2  976.63   601.7  978.03
   611.2  980.67   639.8  984.18   668.4  990.88   793.8 1001.78   832.7 1003.71
   842.4 1005.68   871.6 1015.85   881.3 1017.35   900.8    1019    1037 1037.62
  1085.6 1040.28    1144 1053.32  1221.8 1068.06  1328.8 1087.63  1387.2 1096.88
#Mann= 3 , 0 , 0
       0      .1       0   584.5    .045       0   601.7      .1       0
Bank Sta=584.5,601.7
XS Rating Curve= 0 ,0
Exp/Cntr=0.3,0.1

Type RM Length L Ch R = 1 ,3969.3  ,859.8,825,788.4
XS GIS Cut Line= 4
     1816352.358      303339.805     1816779.441      303478.694
     1816953.052      303693.972     1817609.302      303777.305
#Sta/Elev= 30
       0 1174.16    29.3 1166.73    97.6 1142.03   156.2 1116.78   195.3 1098.39
   214.8 1091.04   273.4 1074.52   361.2  1055.3   380.8 1049.42     410 1034.59
   449.1 1010.73   477.7 1000.58   515.9  990.34     554  982.45  616.89  975.13
   620.8  974.98     635  976.49   668.4   986.1   687.5  988.84   754.8  992.02
   803.5   992.4   871.6 1002.42   900.8 1003.79     930 1003.24   949.4  1004.8
   988.3 1017.08  1027.2 1020.69  1163.4 1037.85  1319.1 1063.84  1387.2 1077.68
#Mann= 3 , 0 , 0
       0      .1       0  616.89    .045       0     635      .1       0
Bank Sta=616.89,635
XS Rating Curve= 0 ,0
Exp/Cntr=0.3,0.1

Type RM Length L Ch R = 1 ,3144.2  ,1218.4,1218,1216.5
XS GIS Cut Line= 3
     1816685.468      304661.019     1817258.608      304211.333
     1817795.955       303832.55
#Sta/Elev= 30
       0 1158.18    97.1 1144.67   165.1 1138.18   242.8 1135.05   262.3 1132.76
   301.1 1125.85   514.8 1073.68   534.2 1066.69   563.4 1050.06   631.4 1001.99
   641.1  997.68   660.5   993.8   699.4  974.11   709.1  973.18   714.4  974.32
   748.1  985.59   816.8  985.84   826.6  987.89   856.1  999.13   865.9  1001.4
   934.6  1007.9     964 1018.02   973.8 1019.74  1013.1 1021.36  1022.9 1023.28
  1052.3  1034.8  1150.4 1057.11    1278 1077.08  1327.1 1092.82  1385.9 1105.39
#Mann= 3 , 0 , 0
       0      .1       0   699.4    .045       0   714.4      .1       0
Bank Sta=699.4,714.4
XS Rating Curve= 0 ,0
Exp/Cntr=0.3,0.1

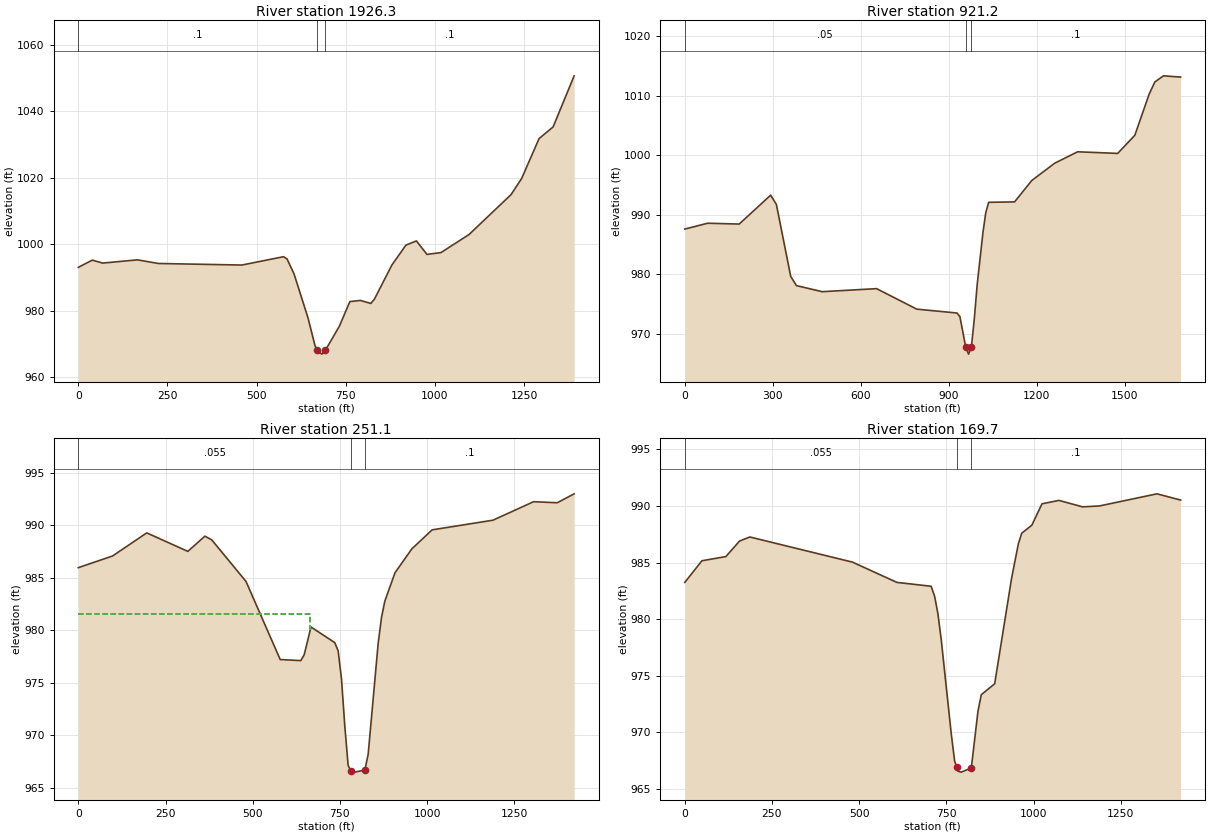
Type RM Length L Ch R = 1 ,1926.3  ,997,1005.1,1012.6
XS GIS Cut Line= 3
     1817353.413       305673.84     1817892.289      305207.861
     1818359.364      304716.043
#Sta/Elev= 30
       0  993.08      39  995.25    68.3  994.36   165.9  995.33   224.5  994.24
   458.7  993.77   575.8  996.28   585.5  995.58   605.1  991.09   644.1  977.92
   663.6  969.65     670   968.1   683.1     967   692.9  968.15   732.1  975.38
   761.6  982.78     791  983.14   820.5  982.23   830.4   983.5   879.5  993.78
   918.8  999.75   948.3 1001.02   977.8  996.97  1017.1  997.51  1095.8 1002.94
  1213.7 1014.93  1243.2 1019.74  1292.4 1031.78  1331.7 1035.28  1390.7 1050.63
#Mann= 3 , 0 , 0
       0      .1       0     670    .045       0   692.9      .1       0
Bank Sta=670,692.9
XS Rating Curve= 0 ,0
Exp/Cntr=0.3,0.1

Type RM Length L Ch R = 1 ,921.2   ,657.5,670.1,682.4
XS GIS Cut Line= 4
     1817704.962      305860.928     1818366.421      305803.636
     1818887.254      305600.511     1819320.734      305423.105
#Sta/Elev= 30
       0  987.62    78.1   988.6   185.5  988.46   292.9  993.31   312.4  991.76
   361.3  979.68   380.8  978.13   468.7  977.11   654.2  977.62   791.4  974.18
   928.7  973.53   938.6  972.91   958.2  967.84     968  966.63   977.8  967.88
   987.6  972.56   997.4  978.29    1017     987  1026.8   990.4  1036.6  992.11
  1124.9  992.18  1183.8  995.78    1262  998.68  1340.1 1000.59  1476.7 1000.32
  1535.2 1003.36    1584 1010.26  1603.5 1012.31  1632.8 1013.34  1691.4 1013.13
#Mann= 3 , 0 , 0
       0     .05       0   958.2    .045       0   977.8      .1       0
Bank Sta=958.2,977.8
XS Rating Curve= 0 ,0
Exp/Cntr=0.3,0.1

Type RM Length L Ch R = 1 ,251.1   ,80.6,81.4,82.5
XS GIS Cut Line= 4
     1817744.025      305989.574     1818402.011       306272.56
     1818570.414      306309.018     1819091.247      306194.435
#Sta/Elev= 30
       0  985.97    98.1  987.08   196.2  989.28     314  987.52     363  988.97
   382.7  988.61   480.8  984.66   578.9  977.22   637.8  977.12   647.6  977.67
   667.2  980.32   735.4  978.83     745  978.05   754.6  975.38   764.1   970.9
   773.7  967.14  781.06  966.65   792.8   966.5   821.6   966.7   831.1  968.19
   859.8  978.76   869.4  981.23     879  982.79     908  985.48   956.4  987.76
  1014.6  989.57  1189.1  990.49  1305.5  992.25  1373.4  992.15  1421.8     993
#Mann= 3 , 0 , 0
       0    .055       0  781.06    .045       0   821.6      .1       0
#XS Ineff= 2 , 0
          665.22  981.53
Permanent Ineff=
       F       F
Bank Sta=781.06,821.6
XS Rating Curve= 0 ,0
Exp/Cntr=0.3,0.1

Type RM Length L Ch R = 1 ,169.7   ,165.4,169.7,174.1
XS GIS Cut Line= 4
     1817704.094       306062.49      1818362.08      306345.477
     1818530.483      306381.935     1819051.316      306267.352
#Sta/Elev= 30
       0  983.25    49.1  985.16   117.7  985.53     157   986.9   186.4  987.26
   480.8  985.04   608.3  983.25   706.4  982.91   716.3  982.04   725.8   980.5
   735.4  978.18   764.1  969.88   773.7  967.49  779.17  966.97   783.3  966.58
   792.8   966.5   821.6  966.87   840.7  971.88   850.3  973.34   888.6   974.3
     937   983.6   956.4  986.64   966.1  987.59   995.2   988.3  1024.3  990.19
  1072.8  990.49  1140.7  989.92  1189.1     990    1354  991.07  1421.8  990.52
#Mann= 3 , 0 , 0
       0    .055       0  779.17    .045       0   821.6      .1       0
Bank Sta=779.17,821.6
XS Rating Curve= 0 ,0
Exp/Cntr=0.3,0.1

Chan Stop Cuts=-1
Use User Specified Reach Order=0
Composite Channel Slope=5